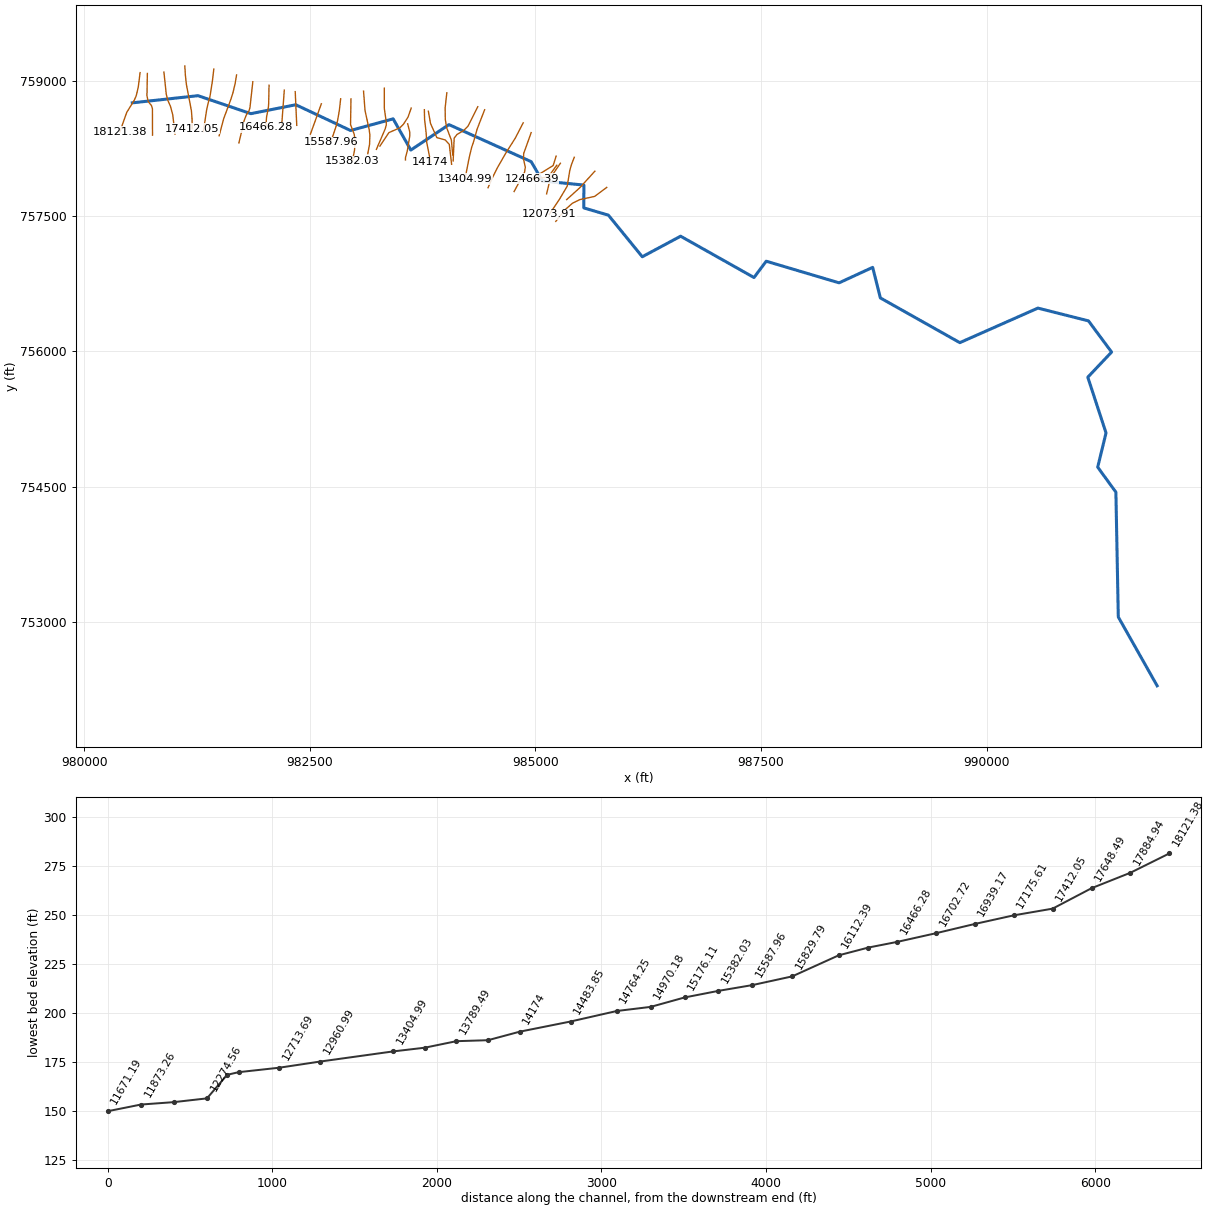
--- 61_ras.prj (project) ---

Proj Title=61
Current Plan=p01
Default Exp/Contr=0.3,0.1
English Units
Geom File=g01
Flow File=f01
Plan File=p01
Y Axis Title=Elevation
X Axis Title(PF)=Main Channel Distance
X Axis Title(XS)=Station
BEGIN DESCRIPTION:
RFD model 61 exported to HEC-RAS
END DESCRIPTION:

--- 61_ras.p01 (plan) ---

Plan Title=Plan 01
Program Version=4.10
Short Identifier=Plan 01
Geom File=g01
Flow File=f01
Subcritical Flow
Calc Critical at every XS
Secant Critical Depth

--- 61_ras.f01 (steady flow) ---

Flow Title=Flow 01
Program Version=5.01
Number of Profiles= 6
Profile Names=10yr,25yr,50yr,100yr,100plus,500yr
River Rch & RM=61,69,18121.38
  107.29  200.73  300.01  407.67   595.2 1296.66
River Rch & RM=61,69,16702.72
  108.98  203.93  304.83  414.26  604.83 1314.87
River Rch & RM=61,69,16466.28
  114.04  213.49  319.22  433.91  633.51  1368.9
River Rch & RM=61,69,16292.61
  121.13  226.89   339.4  461.48  673.76 1444.05
River Rch & RM=61,69,16112.39
  122.78  230.01   344.1  467.91  683.14  1461.5
River Rch & RM=61,69,15829.79
  172.48  323.92  485.51     661  965.06  1970.9
River Rch & RM=61,69,15587.96
  183.29  344.41  516.45  703.34 1026.87 2080.07
River Rch & RM=61,69,15382.03
  191.74  360.43  540.64  736.42 1075.18 2164.69
River Rch & RM=61,69,15176.11
  199.28  374.78  562.34  766.17  1118.6 2240.67
River Rch & RM=61,69,14970.18
  201.63  379.26  569.14  775.51 1132.24 2264.55
River Rch & RM=61,69,14764.25
  217.09  408.65  613.59  836.39 1221.13 2418.34
River Rch & RM=61,69,14483.85
  221.34  416.76  625.89   853.3 1245.82 2461.06
River Rch & RM=61,69,   14174
  223.28  420.48  631.53  861.04 1257.12 2480.55
River Rch & RM=61,69,13981.74
  228.75  430.91  647.34  882.76 1288.84 2535.14
River Rch & RM=61,69,13789.49
  314.14  593.47  893.48  1220.2 1781.49 3357.36
River Rch & RM=61,69,13597.24
  315.29  595.67  896.81 1224.78 1788.18 3368.35
River Rch & RM=61,69,13404.99
  321.11  606.84  913.81 1248.18 1822.35 3424.63
River Rch & RM=61,69,12960.99
  330.36  624.62  940.92 1285.56 1876.92 3514.54
River Rch & RM=61,69,12713.69
  332.89  629.49  948.35 1295.81 1891.89 3539.19
River Rch & RM=61,69,12466.39
  333.21   630.1  949.27 1297.09 1893.75 3542.26
River Rch & RM=61,69,12396.76
  335.69   634.9  956.62 1307.26  1908.6 3566.83
River Rch & RM=61,69,12274.56
   341.5   646.1  973.71 1330.85 1943.04  3623.4
River Rch & RM=61,69,12073.91
  342.27  647.59  975.99 1334.01 1947.65 3631.02
River Rch & RM=61,69,11873.26
  342.42  647.89  976.44 1334.63 1948.57 3632.54
River Rch & RM=61,69,11671.19
  355.28   672.8 1014.59 1387.45 2025.68 3759.57
River Rch & RM=61,69,11469.13
  363.59  688.84 1039.11 1421.34 2075.16 3840.35
River Rch & RM=61,69,11267.07
  367.22  695.88 1049.89 1436.26 2096.94 3876.03
River Rch & RM=61,69,11065.01
  369.15  699.63 1055.66 1444.28 2108.65 3895.31
River Rch & RM=61,69,10862.94
  370.33  701.93  1059.2  1449.2 2115.83 3907.15
River Rch & RM=61,69,10724.58
  372.99  707.11 1067.16 1460.27 2131.99 3933.75
River Rch & RM=61,69,10377.19
  375.17  711.38 1073.75 1469.43 2145.37 3955.86
River Rch & RM=61,69,10079.91
  380.85  722.49 1090.85 1493.23 2180.11 4013.12
River Rch & RM=61,69,9839.648
  382.88  726.45 1096.96 1501.74 2192.54  4033.6
River Rch & RM=61,69,9599.389
  384.32  729.28 1101.32 1507.82 2201.41  4048.2
River Rch & RM=61,69,9359.129
  389.81  740.02 1117.87 1530.86 2235.05  4103.5
River Rch & RM=61,69, 9118.87
  392.98  746.22 1127.43 1544.16 2254.48 4135.38
River Rch & RM=61,69, 8878.61
  394.53  749.28 1132.15 1550.76 2264.11 4151.29
River Rch & RM=61,69,8638.351
  398.78  757.62 1145.04 1568.75 2290.37 4194.54
River Rch & RM=61,69,8398.091
  401.45  762.87 1153.17  1580.1 2306.94 4221.85
River Rch & RM=61,69,8157.832
  403.27  766.46 1158.72 1587.85 2318.26 4240.49
River Rch & RM=61,69,7917.572
  406.08  771.98 1167.26 1599.77 2335.66 4269.11
River Rch & RM=61,69,7677.313
  407.06  773.91 1170.24 1603.93 2341.74 4279.11
River Rch & RM=61,69,7437.053
  411.95  783.53 1185.12 1624.72  2372.1 4328.96
River Rch & RM=61,69,7196.794
  413.33  786.26 1189.35 1630.64 2380.74 4343.17
River Rch & RM=61,69,6842.115
  416.51  792.53 1199.06 1644.22 2400.56 4375.76
River Rch & RM=61,69,6538.427
  463.13  884.78 1342.29 1844.91 2693.57 4855.33
River Rch & RM=61,69,6132.874
  470.22  898.87  1364.2 1875.68 2738.49 4928.48
River Rch & RM=61,69,5751.111
  474.79  907.95 1378.35 1895.54 2767.49 4975.66
River Rch & RM=61,69,5494.697
  475.97  910.29 1381.98 1900.65 2774.95 4987.77
River Rch & RM=61,69,5301.327
   477.4  913.13 1386.41 1906.87 2784.03 5002.54
River Rch & RM=61,69,5120.886
  705.27 1353.98 2061.44 2840.74 4147.48 7071.55
River Rch & RM=61,69,4940.444
  705.86 1355.17 2063.29 2843.34 4151.28 7077.41
River Rch & RM=61,69,4804.895
  976.47 1878.95 2865.82 3953.66 5772.34 9413.11
River Rch & RM=61,69,4528.184
  978.01 1882.04 2870.65 3960.47 5782.28 9427.77
River Rch & RM=61,69,4034.195
  979.77 1885.57 2876.17 3968.24 5793.63 9444.51
River Rch & RM=61,69,3540.206
  981.75 1889.53 2882.37 3976.98 5806.39 9463.34
River Rch & RM=61,69,3046.217
  983.74 1893.49 2888.57 3985.72 5819.15 9482.14
River Rch & RM=61,69,2552.228
 1000.43 1926.89 2940.81 4059.35 5926.65 9640.39
River Rch & RM=61,69, 2058.24
  1002.8 1931.66  2948.3 4069.92 5942.09 9663.21
River Rch & RM=61,69, 1650.96
 1007.12 1940.33  2961.9 4089.14 5970.14 9704.65
River Rch & RM=61,69,1424.802
 1009.16 1944.44 2968.35 4098.25 5983.45 9724.31
River Rch & RM=61,69,868.3371
 1012.59 1951.33 2979.18 4113.56  6005.8 9757.38
River Rch & RM=61,69,287.6631
 1025.35 1977.05  3019.6 4170.77 6089.32 9881.02
River Rch & RM=61,69,       0
 1025.77  1977.9 3020.95 4172.67  6092.1 9885.13
Boundary for River Rch & Prof#=61,69,1
Up Type= 0
Dn Type= 2
Boundary for River Rch & Prof#=61,69,2
Up Type= 0
Dn Type= 2
Boundary for River Rch & Prof#=61,69,2
Up Type= 0
Dn Type= 2
Boundary for River Rch & Prof#=61,69,2
Up Type= 0
Dn Type= 2
Boundary for River Rch & Prof#=61,69,2
Up Type= 0
Dn Type= 2
Boundary for River Rch & Prof#=61,69,2
Up Type= 0
Dn Type= 2

--- 61_ras.g01 (geometry) ---

Geom Title=61
Program Version=4.10

River Reach=61,69
Reach XY= 30
980532.551166283758754.078068233981260.499228344758833.313317298
981846.333418805758634.158613067982344.250085475758732.769724187
982951.194529893 758447.35305754983423.416752131758576.519724186
983619.250085475758230.686390857984042.166752117758512.630835304
984953.277863251758102.214168647985077.203297274757888.317205063
985537.305641026757842.491946434985536.594596956757589.583600079
985809.050237435757509.139596623986184.562656284757048.218076766
986609.559026749757275.880591372987422.771763416756817.871839364
987558.138974369756998.741946422988365.983095501756759.072107024
988737.906260462756930.538215791988823.344899538756591.865646576
989703.939199108756096.161807624990569.140711233756478.947809366
991129.666752132756337.630835309991385.916752131 755991.79750197
991122.329024914755713.190900793 991324.37309793755095.472816136
991232.020370381754716.311749713991433.706034199754439.042887209
991460.362294931753055.555890377991890.908071582 752293.14298809

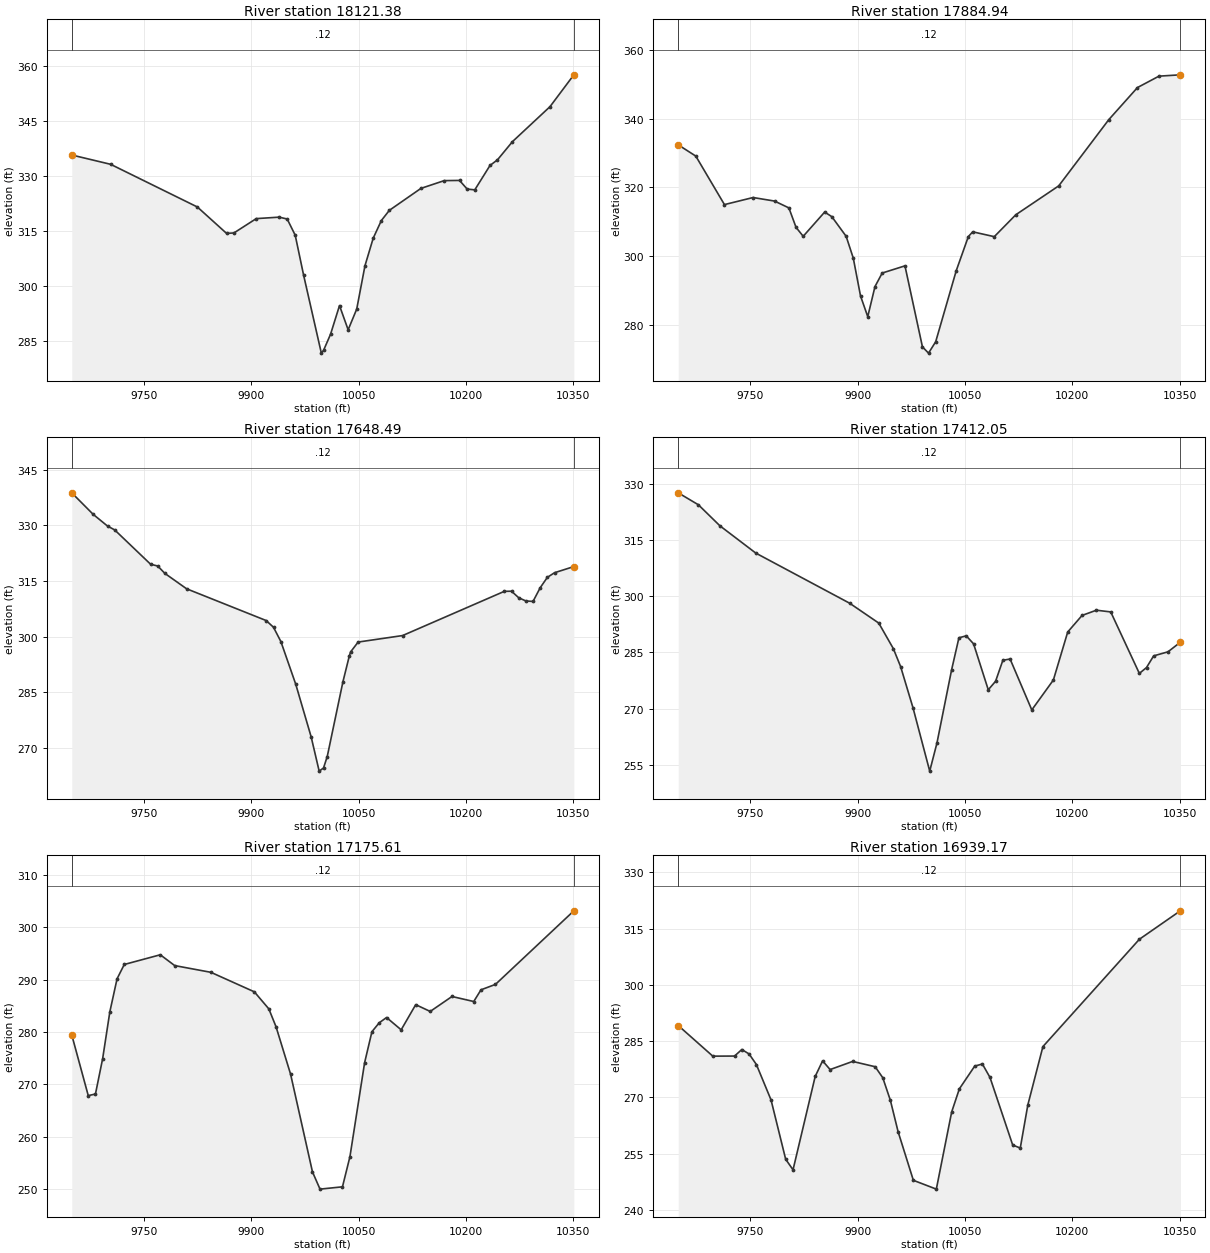
Type RM Length L Ch R = 1 ,18121.38,236.442400,236.442400,236.442400
XS GIS Cut Line= 6
980618.905329805759088.993621696980598.257653009 758926.16611777
980575.243895531 758830.02431226980555.015519254758784.341493036
980470.703740588758648.416039848980394.861069386758433.231404698
#Sta/Elev= 30
9649.065335.60139703.376333.06539824.621 321.4279865.451314.23069875.735314.3446
9906.978318.25589939.058318.65489950.233318.14319961.435 313.7299973.245302.7704
9997.958281.5772   10001282.310310010.84286.729710023.35294.546710035.43287.9367
10047.41293.584410058.94   305.410070.47312.921410081.88317.734710093.02320.5109
10137.19326.498310169.74328.614410191.15328.667610201.81 326.31110212.47326.0975
10233.71332.7422 10244.2334.286910265.18339.253810317.63348.786210350.95357.4631
#Mann= 3 , 0 , 0
9649.065    0.12       09649.065    0.12       010350.95    0.12       0
#XS Ineff= 2 , 0
       0                               0
Bank Sta=9649.065,10350.95
Exp/Cntr=0.3,0.1

Type RM Length L Ch R = 1 ,17884.94,236.442400,236.442400,236.442400
XS GIS Cut Line= 6
980699.403571361759079.529562659980694.737515192758833.702604832
980708.774437413758767.916110246980744.824389376758724.156295616
 980755.58345992758688.198578813980756.505539731758395.217366452
#Sta/Elev= 30
9649.213332.34879673.759329.07149713.787314.95319753.814317.01149783.835315.9816
9803.849313.99189813.856308.32459823.859305.72639853.864312.78249863.866311.4345
 9883.87305.72079893.871299.35019903.961 288.3659914.064282.33649924.167291.0968
9934.269295.03269966.059297.12139990.495273.5349    9999271.716610009.01275.0311
10037.76295.732210054.65305.648410060.78307.026310090.89305.620310120.96311.9936
10180.97320.408110250.98339.697610291.01349.026510321.05352.343710350.87352.7293
#Mann= 3 , 0 , 0
9649.213    0.12       09649.213    0.12       010350.87    0.12       0
#XS Ineff= 2 , 0
       0                               0
Bank Sta=9649.213,10350.87
Exp/Cntr=0.3,0.1

Type RM Length L Ch R = 1 ,17648.49,236.442400,236.442400,236.442400
XS GIS Cut Line= 6
980882.817645321759094.789427564980908.801733911758851.380312746
980923.188126371758788.473263473980955.209178206758716.152560578
980980.768126612758620.973928981981005.725195613758408.062613071
#Sta/Elev= 30
9649.061338.72689678.949332.94039699.015329.78289709.049 328.7459759.214319.5076
9769.247319.01959779.301317.02549809.569312.89559920.819304.34389931.066 302.536
9941.408298.67499962.203287.17279983.702273.03549994.903 263.805   10001 264.652
 10006.2267.737910028.17287.898510037.15294.882910038.92295.911610049.36298.5513
10111.58300.304310253.77312.2074 10263.8312.241210273.82310.485410283.84309.6192
10293.87309.486110303.89313.176510313.91 315.97310323.94317.218610350.93318.8714
#Mann= 3 , 0 , 0
9649.061    0.12       09649.061    0.12       010350.93    0.12       0
#XS Ineff= 2 , 0
       0                               0
Bank Sta=9649.061,10350.93
Exp/Cntr=0.3,0.1

Type RM Length L Ch R = 1 ,17412.05,236.442300,236.442300,236.442300
XS GIS Cut Line= 6
981114.310539505  759163.1705337981120.827606046759058.497809357
981132.667636773758954.718127223981188.110993445 758663.56870194
981194.684468303758572.512960556981195.789970586758467.741831497
#Sta/Elev= 30
9649.061327.52589677.286324.33269707.344318.73419757.457311.47059888.646298.1152
 9929.37292.81899949.733286.02219959.914 281.2379977.303270.213510000.62253.3668
10010.76260.8767 10031.2280.343210041.45288.8956 10051.7289.420210061.95287.2806
10082.46275.046210092.71277.316210102.88282.909310112.99283.241710143.32 269.675
10173.49277.649510193.54290.437110213.59294.858310233.65296.247110253.68295.7888
10293.68279.401710303.68280.967110313.68284.081410333.68285.155210350.94287.7073
#Mann= 3 , 0 , 0
9649.061    0.12       09649.061    0.12       010350.94    0.12       0
#XS Ineff= 2 , 0
       0                               0
Bank Sta=9649.061,10350.94
Exp/Cntr=0.3,0.1

Type RM Length L Ch R = 1 ,17175.61,236.442400,236.442400,236.442400
XS GIS Cut Line= 6
981435.824340155759127.874778414981419.350536434758989.478415019
981392.831993989758821.472162868981370.641958558758741.583017689
981355.180317246758668.098503124981319.948932558758436.423596056
#Sta/Elev= 30
 9649.03279.43629672.067267.83469682.137268.13229692.208274.91279702.278283.8825
9712.349290.1802 9722.42292.92049772.772294.77799792.938292.70829843.557291.4206
9904.299287.68589924.547284.42259934.671280.98179954.918271.94419985.547253.2339
9996.082249.939910027.48250.381310037.93256.153610058.44274.136810068.66280.0569
10078.88281.7664 10089.1282.775910109.54280.419110129.87285.232210150.15283.9357
10180.58286.7941   10211285.835510221.14288.074410241.35  289.1110350.95303.1853
#Mann= 3 , 0 , 0
 9649.03    0.12       0 9649.03    0.12       010350.95    0.12       0
#XS Ineff= 2 , 0
       09860.144                       0
Bank Sta=9649.03,10350.95
Exp/Cntr=0.3,0.1

Type RM Length L Ch R = 1 ,16939.17,236.442400,236.442400,236.442400
XS GIS Cut Line= 6
981688.028367196759062.651952698981672.102161189758967.725466478
981648.128274501758865.877982023 981624.56007909758792.194314502
981545.422427033 758578.84543554981494.908440934758389.425344578
#Sta/Elev= 30
9649.038289.15879697.356280.99399727.776281.01979737.915282.7601 9748.08281.5806
9758.313278.76519778.778269.32759799.244253.51129809.526250.69479840.519275.5901
9850.865279.74169861.364277.41759892.862279.58639924.359278.17519934.994275.2387
9945.683269.17639956.371260.89049977.748247.894710009.87245.543710031.33266.1252
10042.06272.273410063.51 278.33410074.24278.9082 10084.9275.316410116.64257.2984
10127.22256.4955 10137.8267.988310158.89283.546210293.76312.158610350.97319.7355
#Mann= 3 , 0 , 0
9649.038    0.12       09649.038    0.12       010350.97    0.12       0
#XS Ineff= 2 , 0
       09894.296                       0
Bank Sta=9649.038,10350.97
Exp/Cntr=0.3,0.1

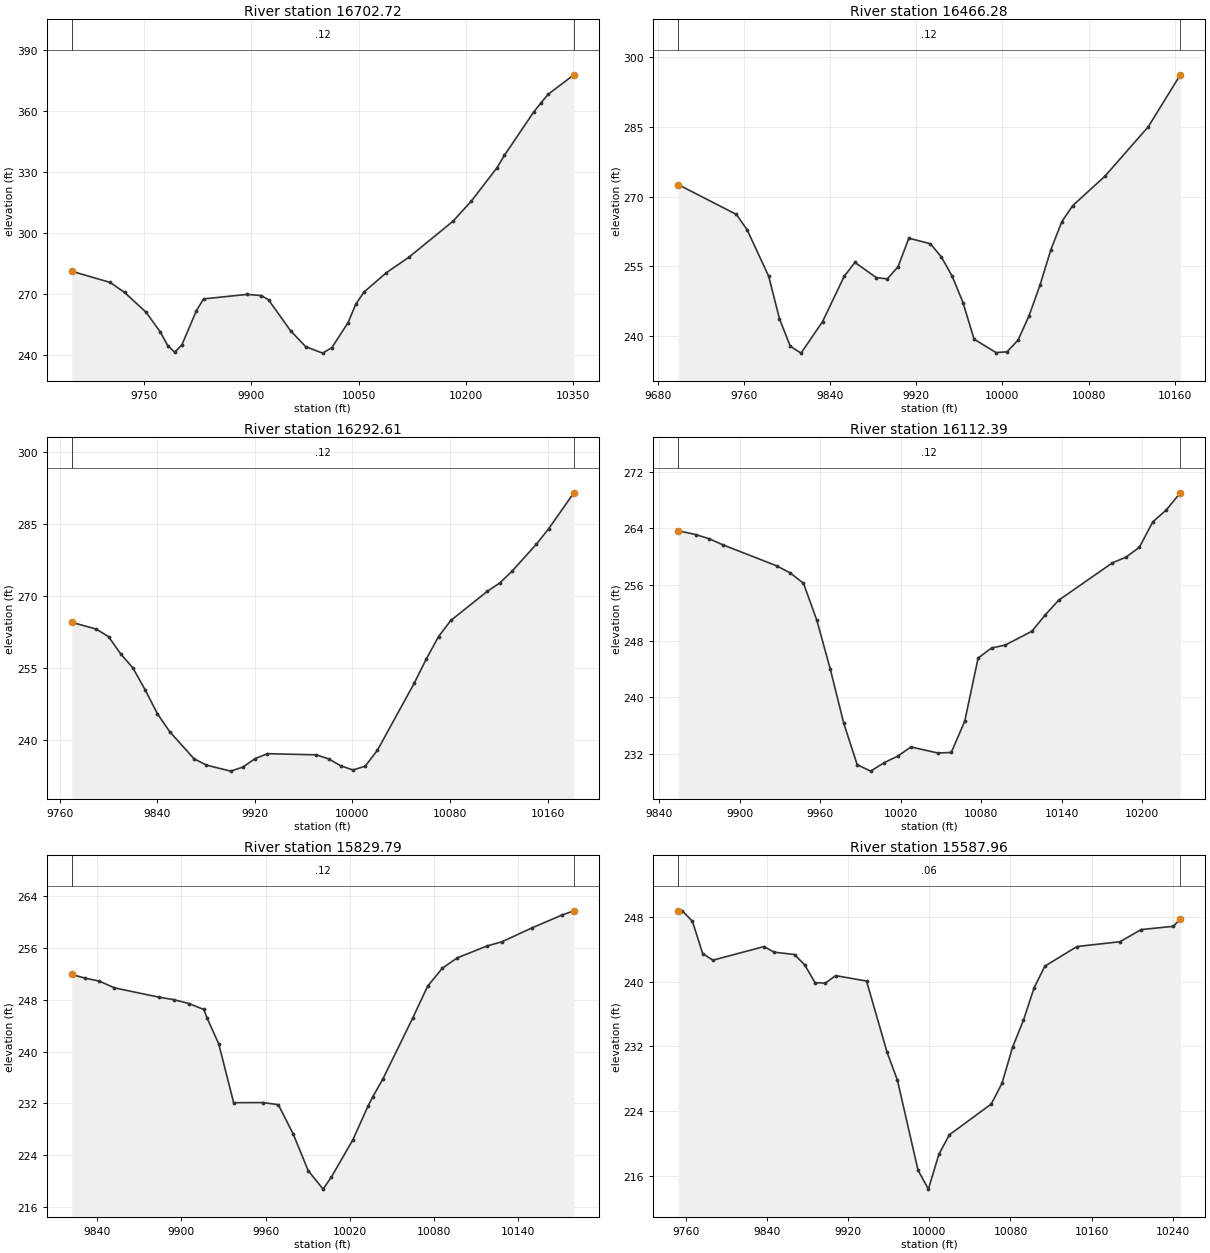
Type RM Length L Ch R = 1 ,16702.72,236.442400,236.442400,236.442400
XS GIS Cut Line= 6
981868.172380772 758988.42483326981836.394630141758699.621974368
981825.226514336758664.984435427981794.463447164758616.236679269
981773.051777605758560.076747084981714.083264208758310.102725312
#Sta/Elev= 30
  9649.1281.13719702.768 275.626 9722.86270.71219752.996260.94499773.087 251.105
9783.133244.55099793.179241.18839803.224245.03839823.315261.70679833.361267.5139
9893.748269.7171 9913.97 269.1659924.128267.06689955.112251.77079976.126243.9908
9999.845240.8052 10012.7243.532310035.26 255.79810046.17264.922110057.58270.8956
10088.86 280.417   10120287.942210182.06305.785510207.79315.749210243.51332.1097
10253.76338.148510294.72359.517510304.96364.037410315.21368.353610350.95377.8756
#Mann= 3 , 0 , 0
  9649.1    0.12       0  9649.1    0.12       010350.95    0.12       0
#XS Ineff= 2 , 0
       0 9872.67                       0
Bank Sta=9649.1,10350.95
Exp/Cntr=0.3,0.1

Type RM Length L Ch R = 1 ,16466.28,173.669500,173.669500,173.669500
XS GIS Cut Line= 6
982047.999318212 758948.93520762982044.046950221758751.810058355
982041.763542026758714.332483664982037.879616171758686.327704817
982020.097786129758595.521294549982012.453928769758485.319865227
#Sta/Elev= 30
9699.181272.56039753.127266.16049763.129262.85299783.133252.87449793.135243.7458
9803.137237.84929813.139236.35979833.143 243.1379853.147252.84099863.149255.8499
9883.153252.56759893.155252.31339903.168254.89879913.187261.05899933.224259.8532
9943.314257.0553 9953.41252.88919963.523247.20019973.751 239.3629994.208236.4722
10004.39236.653610014.56239.158310024.73244.3707 10034.9250.942810045.07 258.603
10055.23 264.61610065.25268.029310095.33274.398410135.42284.990510165.17296.1445
#Mann= 3 , 0 , 0
9699.181    0.12       09699.181    0.12       010165.17    0.12       0
#XS Ineff= 2 , 0
       09909.372                       0
Bank Sta=9699.181,10165.17
Exp/Cntr=0.3,0.1

Type RM Length L Ch R = 1 ,16292.61,180.221900,180.221900,180.221900
XS GIS Cut Line= 2
982216.952350289758895.047291383982186.652036101758484.309698701
#Sta/Elev= 30
9769.759264.54879789.861263.13669799.888261.57019809.915257.95659819.942255.0264
9829.969250.45769839.996245.48449850.024 241.7489870.078236.07299880.105234.7589
 9900.16233.49459910.187234.34689920.214236.12029930.241237.1362 9970.35236.8973
9980.377236.05519990.404234.617710000.43233.727810010.46234.532810020.49237.8597
10050.57251.800910060.59256.914610070.62261.587210080.65264.934410110.73271.0433
10120.76272.748910130.78275.183910150.84280.848510160.87284.051210181.61291.5781
#Mann= 3 , 0 , 0
9769.759    0.12       09769.759    0.12       010181.61    0.12       0
#XS Ineff= 2 , 0
       09951.024                       0
Bank Sta=9769.759,10181.61
Exp/Cntr=0.3,0.1

Type RM Length L Ch R = 1 ,16112.39,282.603100,282.603100,282.603100
XS GIS Cut Line= 2
 982338.15360719758878.213783473982354.987115085758504.509908184
#Sta/Elev= 30
9854.241263.63089867.468263.07539877.478262.48099887.488261.63469927.529258.6524
9937.539257.66469947.549256.17669957.559 250.906 9967.57243.9657 9977.58236.3055
 9987.59230.4317  9997.6229.525110007.61230.722110017.62231.634410027.63232.9555
10047.65 232.09710057.66232.173210067.67 236.58310077.68245.566910087.69246.9979
 10097.7247.397910117.72249.364310127.73251.702510137.74253.778110177.78259.0827
10187.79259.8702 10197.8261.282510207.81264.891910217.82266.568310228.32269.0072
#Mann= 3 , 0 , 0
9854.241    0.12       09854.241    0.12       010228.32    0.12       0
#XS Ineff= 2 , 0
       0                               0
Bank Sta=9854.241,10228.32
Exp/Cntr=0.3,0.1

Type RM Length L Ch R = 1 ,15829.79,241.824200,241.824200,241.824200
XS GIS Cut Line= 2
982627.689943016758743.545720309982506.488686115758406.875562385
#Sta/Elev= 30
  9821.8 251.9339830.883251.37789841.511250.89369852.139249.86169884.024 248.413
9894.652248.0267 9905.28  247.449915.909246.5165 9918.31245.16359926.537241.2025
9937.165232.12339958.422232.1361 9969.05231.80389979.678227.24799990.307221.6278
10000.93218.768410006.88220.659310022.19226.417410032.82231.5481 10036.4233.0729
10043.45235.7543 10064.7245.153210075.33250.080610085.96252.911910096.59254.4953
10117.85256.335910128.47256.983510149.73259.116510170.99261.089510179.62261.7563
#Mann= 3 , 0 , 0
  9821.8    0.12       0  9821.8    0.12       010179.62    0.12       0
#XS Ineff= 2 , 0
       0                               0
Bank Sta=9821.8,10179.62
Exp/Cntr=0.3,0.1

Type RM Length L Ch R = 1 ,15587.96,205.928500,205.928500,205.928500
XS GIS Cut Line= 6
982841.685364373758798.914932864982826.939115318 758668.45838374
982808.297654605758560.433835626982806.979834292758555.145103688
982791.745751894758495.762756957982732.035080422758318.509760037
#Sta/Elev= 30
9752.641 248.6619756.581248.74199766.645247.44319776.708243.45869786.772242.6394
 9837.09244.31799847.154243.62849867.281243.33839877.345242.03799887.438239.8597
9897.586239.79799907.733240.72989938.177240.05649958.472231.2261 9968.62227.7957
9988.916216.6611 9999.15214.323210009.48218.6397 10019.8221.041510061.11224.8539
10071.66227.425210082.21231.925810092.77235.205610103.32239.225510113.87 241.899
10145.53244.328310187.74244.917610208.84246.4218 10240.5246.831310247.35247.7554
#Mann= 3 , 0 , 0
9752.641    0.06       09752.641    0.06       010247.35    0.06       0
#XS Ineff= 2 , 0
       0                               0
Bank Sta=9752.641,10247.35
Exp/Cntr=0.3,0.1

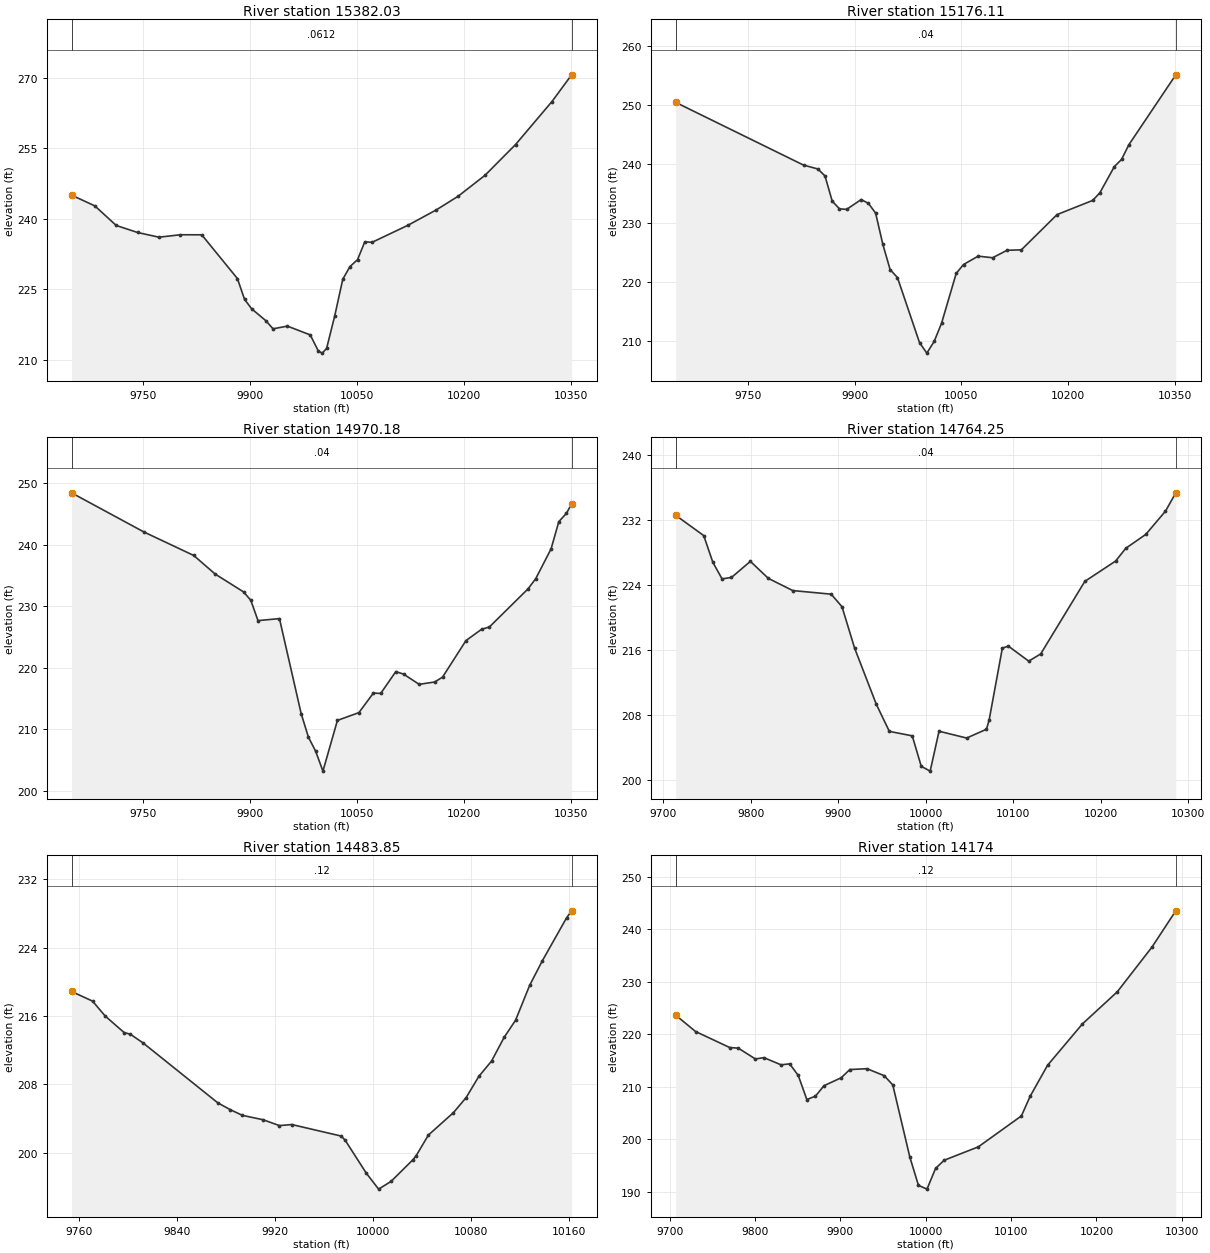
Type RM Length L Ch R = 1 ,15382.03,205.928400,205.928400,205.928400
XS GIS Cut Line= 6
982956.167480863758797.647494785982951.206019549758512.792158442
982992.129680307 758405.09048634983002.018999336758327.156850305
982995.234924404758228.597649418982971.548041193758108.008246514
#Sta/Elev= 30
9649.123245.00699681.781242.7231 9711.79238.55279741.799237.05519771.808236.0533
9801.817236.57349831.826236.56369881.841227.25869891.843222.84029901.845  220.81
 9921.85218.26899931.852216.55159952.023217.1268 9984.07215.25239995.538211.8018
   10001211.375610007.03212.382610018.47219.331310029.73227.1064 10039.8229.7948
10050.45231.279710060.64235.076210070.82234.965310121.21238.593610161.23241.8906
10191.34244.744610229.38249.237910272.12255.771710323.25 264.93110350.87270.6184
#Mann= 3 , 0 , 0
9649.123  0.0612       09649.123  0.0612       010350.87  0.0612       0
#XS Ineff= 2 , 0
       0                               0
Bank Sta=9649.123,10350.87
Exp/Cntr=0.3,0.1

Type RM Length L Ch R = 1 ,15176.11,205.928500,205.928500,205.928500
XS GIS Cut Line= 6
983095.293063287758883.845295954983111.875924697758667.911880062
983156.376793367758465.805631306 983165.47333161758398.345688683
983162.044116164758294.342290524983142.083433913758190.431118569
#Sta/Elev= 30
9649.055250.45999828.424239.84289848.537239.18789858.594238.00369868.679233.7541
9878.836232.43529888.993 232.3439909.307234.00699919.464233.37049929.621231.7199
9939.778226.41419950.002222.14759960.307220.79259991.222209.795910001.53208.0033
10011.83209.987510022.13213.047510042.72221.491610053.01223.009810073.59224.4239
10093.87224.154610114.08225.416410134.19 225.49110184.24231.457610234.38233.8672
10244.41235.161610264.65239.576510274.78   240.8 10284.9 243.25410350.92255.1258
#Mann= 3 , 0 , 0
9649.055    0.04       09649.055    0.04       010350.92    0.04       0
#XS Ineff= 2 , 0
       0                               0
Bank Sta=9649.055,10350.92
Exp/Cntr=0.3,0.1

Type RM Length L Ch R = 1 ,14970.18,205.928400,205.928400,205.928400
XS GIS Cut Line= 6
  983325.6359345758916.484763136983325.780152983758691.425376452
 983347.22890174758541.153628238 983347.06742531758507.080502089
983334.487497357758463.173632019983237.674251132758238.294191929
#Sta/Elev= 30
9649.062248.40689750.558242.05079820.572  238.239850.579235.21469890.653232.2964
9900.694230.93579910.735227.64569940.859227.9723  9971.3 212.5489981.484 208.715
9991.667206.428910001.87203.192510022.23211.436310052.35212.699110072.65 215.871
10082.97215.818110104.12219.3571   10115218.9589 10136.9217.293710158.81217.6749
10169.76218.466710202.61224.402910224.51226.236910235.46226.609810289.74232.8069
10300.53234.463510322.11239.3149 10332.9243.721510343.69245.086510350.92246.6357
#Mann= 3 , 0 , 0
9649.062    0.04       09649.062    0.04       010350.92    0.04       0
#XS Ineff= 2 , 0
       0                10035.36       0
Bank Sta=9649.062,10350.92
Exp/Cntr=0.3,0.1

Type RM Length L Ch R = 1 ,14764.25,280.394300,280.394300,280.394300
XS GIS Cut Line= 6
983623.617737671758695.742610653 983588.50959612758595.934879949
983535.845989616758514.346754552 983497.18568329758477.044456047
983376.218075181 758423.83780416983276.887253667758274.540251955
#Sta/Elev= 30
9714.229232.59999746.267 230.1049756.688226.81489767.201224.77359777.996224.9469
9799.585226.92979820.166224.82959848.032223.33169891.949222.88729904.296221.3396
9918.711216.24479943.511209.32629958.421 205.9899984.602205.4392 9994.89201.6868
10005.06 201.09310015.22206.008910046.76205.167510069.41206.250610072.48207.3876
10087.58 216.24210094.47216.488810117.73214.6409 10131.4215.526610181.86224.4658
10217.04 226.96510228.71228.543910251.53230.249210274.05233.116210285.82235.3695
#Mann= 3 , 0 , 0
9714.229    0.04       09714.229    0.04       010285.82    0.04       0
#XS Ineff= 2 , 0
       0                10031.12       0
Bank Sta=9714.229,10285.82
Exp/Cntr=0.3,0.1

Type RM Length L Ch R = 1 ,14483.85,309.859700,309.859700,309.859700
XS GIS Cut Line= 6
983584.491038322 758521.65155375983607.494510561 758430.52241379
983607.494510561758385.400218278983580.067293644758220.836916998
983560.602817178758150.057002485983559.718068212758120.860287726
#Sta/Elev= 30
9753.936218.8726 9771.11217.74019781.424215.99719796.874214.06339802.051213.8591
9812.365212.84729873.447205.82899883.447205.04559893.451 204.3689910.479203.8496
9923.763203.16619933.867203.29079974.328201.93759977.594201.43429994.665197.6153
10004.83195.7268   10015196.631810032.72199.149410035.34199.601510045.51202.0598
10065.96 204.68410076.34206.449710086.71208.926610097.08210.718210107.45213.5163
10116.73215.506410128.19219.575210138.38222.409510158.39227.494110162.53228.3152
#Mann= 3 , 0 , 0
9753.936    0.12       09753.936    0.12       010162.53    0.12       0
#XS Ineff= 2 , 0
       0                               0
Bank Sta=9753.936,10162.53
Exp/Cntr=0.3,0.1

Type RM Length L Ch R = 1 ,   14174,192.252000,192.252000,192.252000
XS GIS Cut Line= 6
983769.367179999758678.295005788983771.915234196758568.502690491
983788.112126638 758430.88862897983795.937951482 758314.03393975
 983827.04674248758156.351319435983836.383744855758097.432688429
#Sta/Elev= 30
9707.012223.65729730.307  220.549770.307217.49439780.321 217.3779800.349215.3193
9810.363215.56469830.465214.19739840.534214.38359850.603212.18039860.672207.5812
9870.742208.23189880.811210.22489900.949211.73599911.018213.29939931.156213.4584
9951.294212.1299 9961.34210.3812  9981.4196.59419991.431191.243610001.47190.5179
10011.49194.458510021.51196.017510061.58198.570710112.11204.466610122.28208.1952
10142.72214.1142 10183.6221.996110224.48228.117810265.06236.629910292.97243.5359
#Mann= 3 , 0 , 0
9707.012    0.12       09707.012    0.12       010292.97    0.12       0
#XS Ineff= 2 , 0
       0                               0
Bank Sta=9707.012,10292.97
Exp/Cntr=0.3,0.1

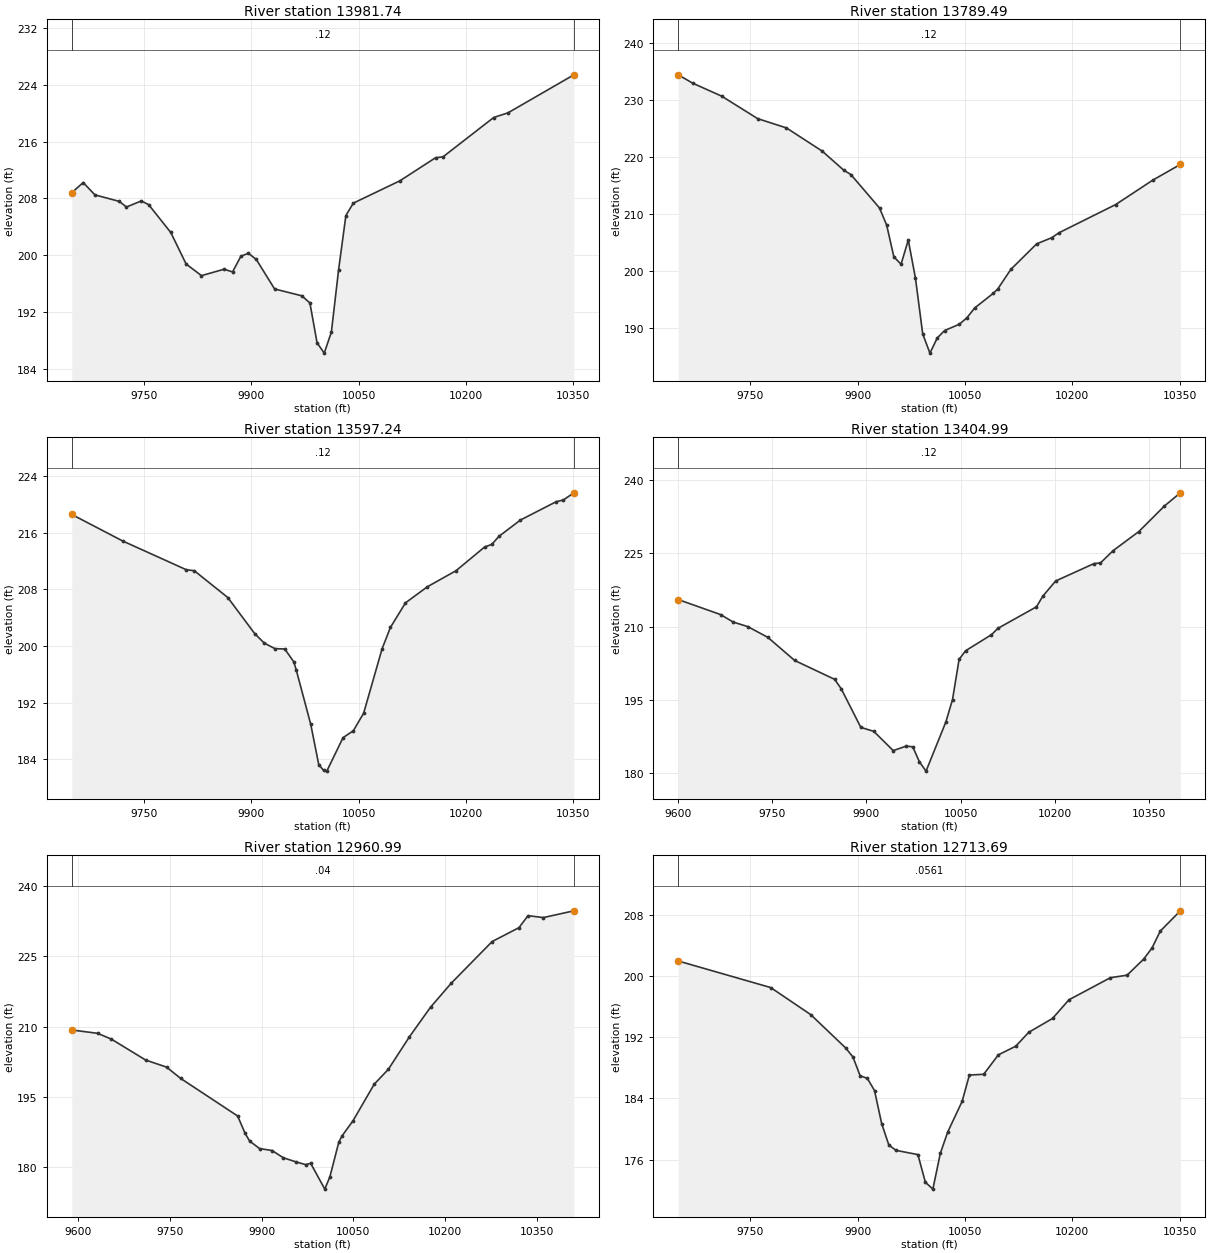
Type RM Length L Ch R = 1 ,13981.74,192.251900,192.251900,192.251900
XS GIS Cut Line= 6
983813.934893328758660.891676368983837.395102305758525.904532285
983907.335243062758368.921583235984001.046938355758342.515413026
984045.772753085758292.971456713 984071.17114249758073.076231806
#Sta/Elev= 30
9649.316208.79439665.256210.22869681.672208.49029715.649207.57369725.751206.7776
 9746.35207.63679756.658207.1194 9787.62203.18769809.064198.74299830.507 197.104
9862.102 198.0099873.924197.62589885.609199.84639896.023200.25789907.073199.3863
9932.623 195.2279970.639194.2599 9981.97193.2498 9991.97187.634810001.98186.1782
10011.98189.148510021.99197.887610032.23205.582210042.61207.323710107.86210.4849
10157.41213.726410167.95213.856210238.65219.398810258.69220.057810350.66225.4172
#Mann= 3 , 0 , 0
9649.316    0.12       09649.316    0.12       010350.66    0.12       0
#XS Ineff= 2 , 0
       0                               0
Bank Sta=9649.316,10350.66
Exp/Cntr=0.3,0.1

Type RM Length L Ch R = 1 ,13789.49,192.252000,192.252000,192.252000
XS GIS Cut Line= 6
984018.322749873758865.193956186983999.880078427758698.703760683
984001.324525906758570.934456802984017.464189891758475.362705363
984068.676118504 758341.79644811984083.781359575758176.602158145
#Sta/Elev= 30
9649.054234.38119669.422232.90989709.765230.65199760.107 226.7119800.251225.0913
9850.322221.02839880.332217.70299890.344216.93089930.392211.08059940.404208.0787
9950.457202.52759960.538201.2345 9970.62205.47429980.701198.75759990.783189.0485
10000.88185.673810011.13 188.32810021.38189.627810041.88190.718810052.53191.8563
 10063.5193.581410089.48196.146610095.76196.914310113.97200.328710150.08204.7971
10170.97205.865910181.42206.746210260.51211.674510312.44215.954710350.88218.6954
#Mann= 3 , 0 , 0
9649.054    0.12       09649.054    0.12       010350.88    0.12       0
#XS Ineff= 2 , 0
       0                               0
Bank Sta=9649.054,10350.88
Exp/Cntr=0.3,0.1

Type RM Length L Ch R = 1 ,13597.24,192.252000,192.252000,192.252000
XS GIS Cut Line= 6
984361.397705767758710.758948593 984252.92331856758495.242955117
984205.227552785758446.961832872984130.805228423758403.328614322
984099.941858612758363.274927313984088.611297773758110.335731847
#Sta/Elev= 30
9649.117218.55099720.323214.80479808.961210.76249820.368  210.619867.139206.8341
9904.692201.75159917.996200.41449932.936199.62259946.807199.56879959.359197.7645
9962.706196.65499983.094188.93899994.302183.2484   10001182.457410005.51182.3419
 10028.2187.060910042.63188.040110057.04190.523910082.78199.600710094.42202.6128
10115.47206.081210146.05208.348110186.09210.615110226.09213.961210236.09214.3249
10246.09215.463110276.09217.762210326.09220.350710336.09220.590110350.76221.6018
#Mann= 3 , 0 , 0
9649.117    0.12       09649.117    0.12       010350.76    0.12       0
#XS Ineff= 2 , 0
       0                               0
Bank Sta=9649.117,10350.76
Exp/Cntr=0.3,0.1

Type RM Length L Ch R = 1 ,13404.99,444.000000,444.000000,444.000000
XS GIS Cut Line= 6
984437.359174567758677.622004653984354.251708872758463.062369645
984317.109748331758329.851242164984292.712304695758257.625683799
984264.537640739758138.557464862984219.785245565757910.191366421
#Sta/Elev= 30
 9600.12215.5489  9667.5212.47899687.785210.9402 9710.54210.03079742.819207.8203
9785.577203.08879849.141199.2313 9859.61197.32669890.946189.39929911.603188.5797
9942.587184.64849963.244185.56039973.695185.42479984.276182.34919994.858180.4452
10026.51190.532810037.04 195.09510047.51 203.31410057.84205.075610099.12208.3582
10109.37 209.657 10170.8214.070110180.99216.265210201.37219.355810262.51222.9117
 10272.7223.045210293.08225.577210333.84229.4631 10374.6234.692910399.89237.3858
#Mann= 3 , 0 , 0
 9600.12    0.12       0 9600.12    0.12       010399.89    0.12       0
#XS Ineff= 2 , 0
       0                               0
Bank Sta=9600.12,10399.89
Exp/Cntr=0.3,0.1

Type RM Length L Ch R = 1 ,12960.99,247.300500,247.300500,247.300500
XS GIS Cut Line= 6
984864.899816332758532.801108446984775.196465366758359.692835648
984672.765813456758198.491164752984578.636247756758034.328410996
984523.830667133757924.534862487984475.031346633757812.925029989
#Sta/Elev= 30
9590.107209.26389632.358208.54659654.712207.31439710.736202.8405  9744.9201.3269
9767.675198.93429860.923190.8856 9872.86187.25859880.474185.53349896.734183.9262
9917.098183.51189935.411181.97219956.419181.07299972.035180.49289980.166180.7801
10003.26 175.26110011.68177.938210026.31185.3896 10031.8186.707410049.36189.8738
10083.93197.678110106.97200.850110141.54207.826910175.89214.128110209.75219.2626
10276.48228.156310320.33231.1269 10335.1233.686510360.06233.2766 10409.9234.7189
#Mann= 3 , 0 , 0
9590.107    0.04       09590.107    0.04       0 10409.9    0.04       0
#XS Ineff= 2 , 0
       0                               0
Bank Sta=9590.107,10409.9
Exp/Cntr=0.3,0.1

Type RM Length L Ch R = 1 ,12713.69,247.300600,247.300600,247.300600
XS GIS Cut Line= 6
984953.418934741758424.048360048984870.093553197758192.402965814
984868.093263149758129.999132162984888.361668852758041.013439703
984880.231938602757985.792279366984763.838522018757770.891768647
#Sta/Elev= 30
9649.113201.94999778.376198.47619834.306194.93959883.005190.59629893.242189.4131
9903.343186.95169913.395186.61029923.448185.01469933.473180.68269943.481177.8943
9953.489177.1992 9984.06176.64549994.526173.0326   10005172.131210015.42176.7976
10025.79179.603610045.97183.613710056.02187.039210076.06 187.14310096.53189.6837
10120.76190.804910138.93192.623610172.36194.447610195.12196.873410253.18 199.769
 10276.4200.091210299.63202.196310311.24203.641110322.85205.859810350.85208.5067
#Mann= 3 , 0 , 0
9649.113  0.0561       09649.113  0.0561       010350.85  0.0561       0
#XS Ineff= 2 , 0
       0                               0
Bank Sta=9649.113,10350.85
Exp/Cntr=0.3,0.1

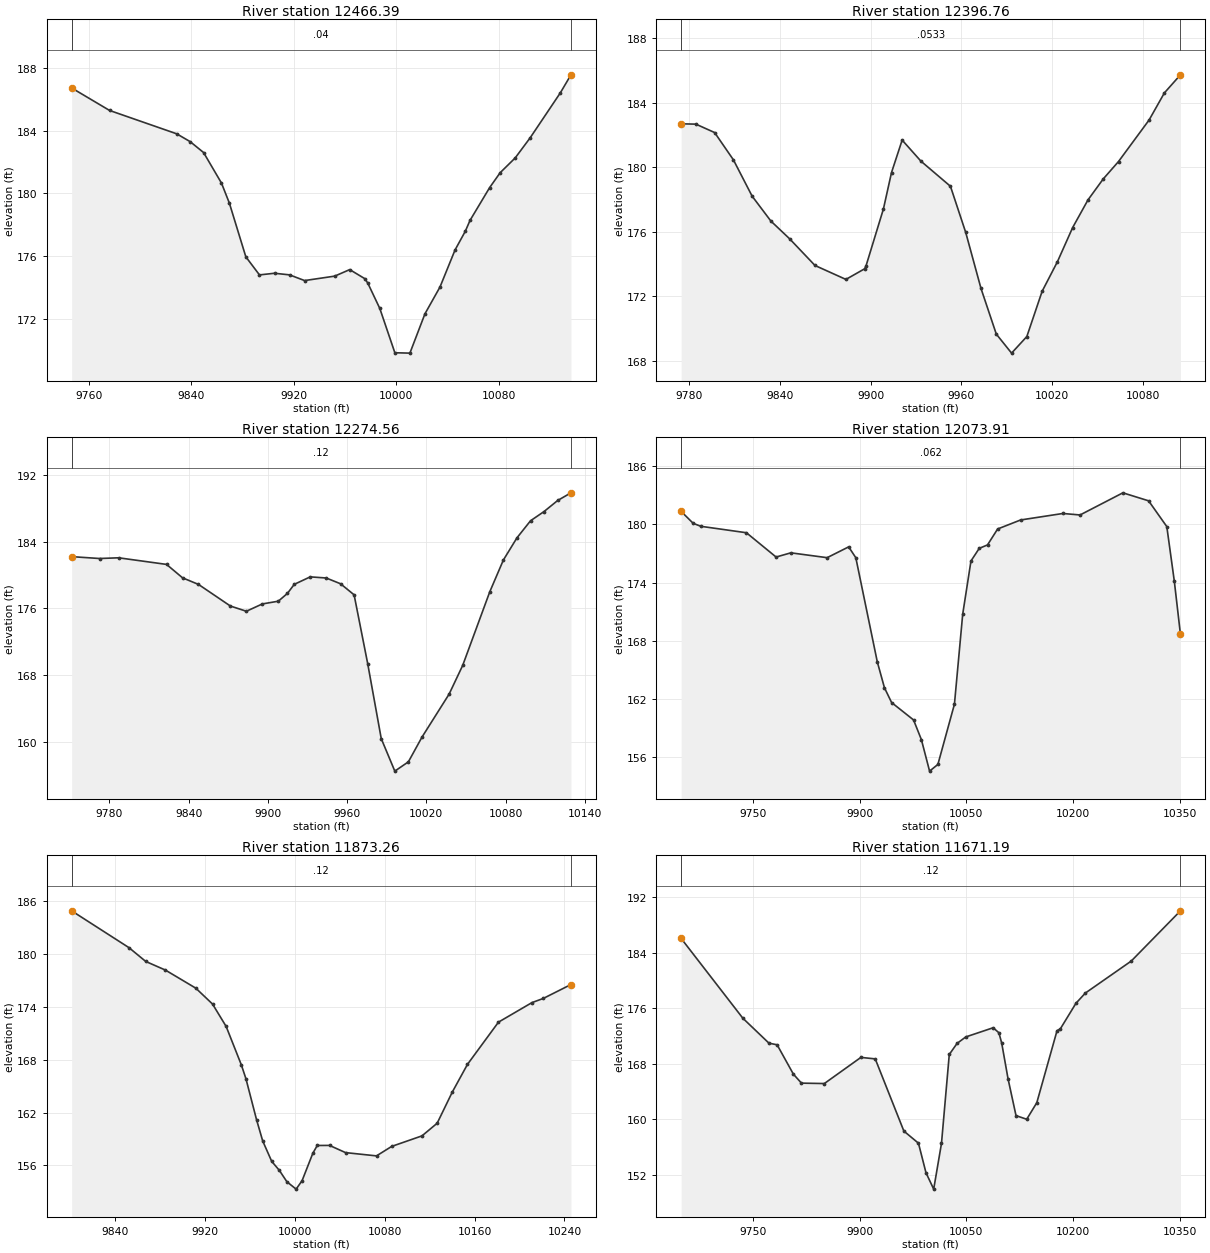
Type RM Length L Ch R = 1 ,12466.39,69.630000,69.630000,69.630000
XS GIS Cut Line= 3
985229.867007613758163.242907703985196.831248373 758059.05320546
984957.957296878757911.662894994
#Sta/Elev= 30
9746.379186.71169776.008185.28069828.461183.79459838.951183.29699849.442182.6039
9863.399180.66499869.583179.38689882.443175.97179893.083174.82169904.834174.9263
9916.584174.82429928.335174.46159951.835174.74349963.586 175.1599975.336174.5836
9977.662174.30569987.087172.68689998.837169.870610010.59169.846810022.34 172.347
10034.09174.052110045.84176.406810053.84177.593910057.59178.295910072.88180.3753
10081.09181.321410092.84182.261810104.59 183.54910128.09   186.410136.37 187.546
#Mann= 3 , 0 , 0
9746.379    0.04       09746.379    0.04       010136.37    0.04       0
#XS Ineff= 2 , 0
       09944.777                       0
Bank Sta=9746.379,10136.37
Exp/Cntr=0.3,0.1

Type RM Length L Ch R = 1 ,12396.76,122.198000,122.198000,122.198000
XS GIS Cut Line= 3
985237.490644395758062.865023851985142.195185035757933.263199121
984974.475176513757907.851076603
#Sta/Elev= 30
9774.534182.68449784.297182.66399796.709182.14229809.121180.45349821.533178.2004
9833.946176.65869846.358175.55869863.142173.90679883.595173.04379896.007173.7035
9896.904173.8809 9908.42177.40679913.785179.66719920.832181.67599933.244180.3713
9952.792178.81329962.906175.9525 9973.02172.48139983.134169.65819993.248 168.477
10003.36169.506110013.48172.308510023.59174.1384 10033.7176.259810043.82177.9692
10053.93179.270110064.05180.349210084.28 182.92110094.39184.598310105.03185.7192
#Mann= 3 , 0 , 0
9774.534  0.0533       09774.534  0.0533       010105.03  0.0533       0
#XS Ineff= 2 , 0
       09925.466                       0
Bank Sta=9774.534,10105.03
Exp/Cntr=0.3,0.1

Type RM Length L Ch R = 1 ,12274.56,200.650900,200.650900,200.650900
XS GIS Cut Line= 3
985276.879434258758084.465327963985166.336701363757921.827743992
 985124.40669927757745.213492632
#Sta/Elev= 30
 9751.35182.18849772.483181.96459786.977182.04869823.251181.25649835.342179.6491
9847.433178.85619871.616176.26349883.707  175.649895.798176.51799907.889176.8447
9914.798177.7816 9919.98178.86659932.072179.76249944.163179.62799955.016178.9365
9965.294 177.6089975.572169.3704 9985.85160.36649996.128156.470510006.41157.5864
10016.68160.541410037.24165.701710047.52169.141110068.07177.980310078.35181.7841
10088.63184.442110098.91186.488610109.19187.599110119.46188.919910129.52189.8392
#Mann= 3 , 0 , 0
 9751.35    0.12       0 9751.35    0.12       010129.52    0.12       0
#XS Ineff= 2 , 0
       09938.694                       0
Bank Sta=9751.35,10129.52
Exp/Cntr=0.3,0.1

Type RM Length L Ch R = 1 ,12073.91,200.650900,200.650900,200.650900
XS GIS Cut Line= 6
985430.972141877758150.803336469985399.805276507758069.375082479
985381.883333147758008.517281349985352.777294225757830.868922745
985268.472376769757687.952853299 985154.31289495757517.823398927
#Sta/Elev= 30
9649.166181.33489666.087180.10629676.795179.79969740.916179.13449782.614176.6298
9803.383177.06339854.355176.56339884.607 177.678 9894.67176.5585 9924.86165.8227
9934.923163.14889944.986161.62629975.832159.83059986.862157.79719998.347 154.554
10010.03155.245610033.28161.4539 10044.9170.737710056.52176.222210068.14177.5247
10079.76177.879210093.99179.521610126.25180.451210185.74181.121310209.83 180.967
10270.04183.250610306.17182.426410331.76179.7682 10342.3174.154210350.94168.6598
#Mann= 3 , 0 , 0
9649.166   0.062       09649.166   0.062       010350.94   0.062       0
#XS Ineff= 2 , 0
       0                               0
Bank Sta=9649.166,10350.94
Exp/Cntr=0.3,0.1

Type RM Length L Ch R = 1 ,11873.26,202.062400,202.062400,202.062400
XS GIS Cut Line= 3
985659.331877857757996.793505356985495.423687696757816.367435634
 985346.76277113757681.683186382
#Sta/Elev= 30
9801.422184.91049852.479 180.7279867.351179.16539884.906178.18149911.927176.1303
9926.838174.32379938.948171.78029952.458167.42299956.582165.83259965.968161.2069
9971.454158.78879979.479156.46729986.325155.43639992.989154.1528 10001.2153.3147
 10006.5154.270810016.07157.383410020.01158.268910030.94158.277810045.18157.4606
10072.74157.088910086.24158.164310113.22159.361810126.72160.794810140.21164.3393
 10153.7167.479210181.27172.271810211.05174.488610221.17174.963710245.78176.5427
#Mann= 3 , 0 , 0
9801.422    0.12       09801.422    0.12       010245.78    0.12       0
#XS Ineff= 2 , 0
       0                               0
Bank Sta=9801.422,10245.78
Exp/Cntr=0.3,0.1

Type RM Length L Ch R = 1 ,11671.19,202.062300,202.062300,202.062300
XS GIS Cut Line= 6
985790.376794732757816.519605405985656.673234938757717.075230344
985492.928934393757681.529768397985410.967880942757641.759659831
985331.765365668 757571.70457843985226.154030192757440.006281038
#Sta/Elev= 30
 9649.12186.06079735.847 174.5519772.569170.95169784.018170.71839806.914166.4792
9818.257 165.1879850.391165.12839901.792168.90079921.942168.68369962.192158.2706
9982.685156.52399993.264152.2601 10004.1149.899910015.05156.4978   10026169.3205
10036.96170.9204 10049.2171.852710087.65173.174210095.74172.456410099.69170.9632
10108.58165.825310119.81160.502610134.84159.977110149.02162.365910177.46172.7536
10182.03173.007310204.07 176.70810217.27178.180610281.77182.795810350.92190.0402
#Mann= 3 , 0 , 0
 9649.12    0.12       0 9649.12    0.12       010350.92    0.12       0
#XS Ineff= 2 , 0
       0                               0
Bank Sta=9649.12,10350.92
Exp/Cntr=0.3,0.1