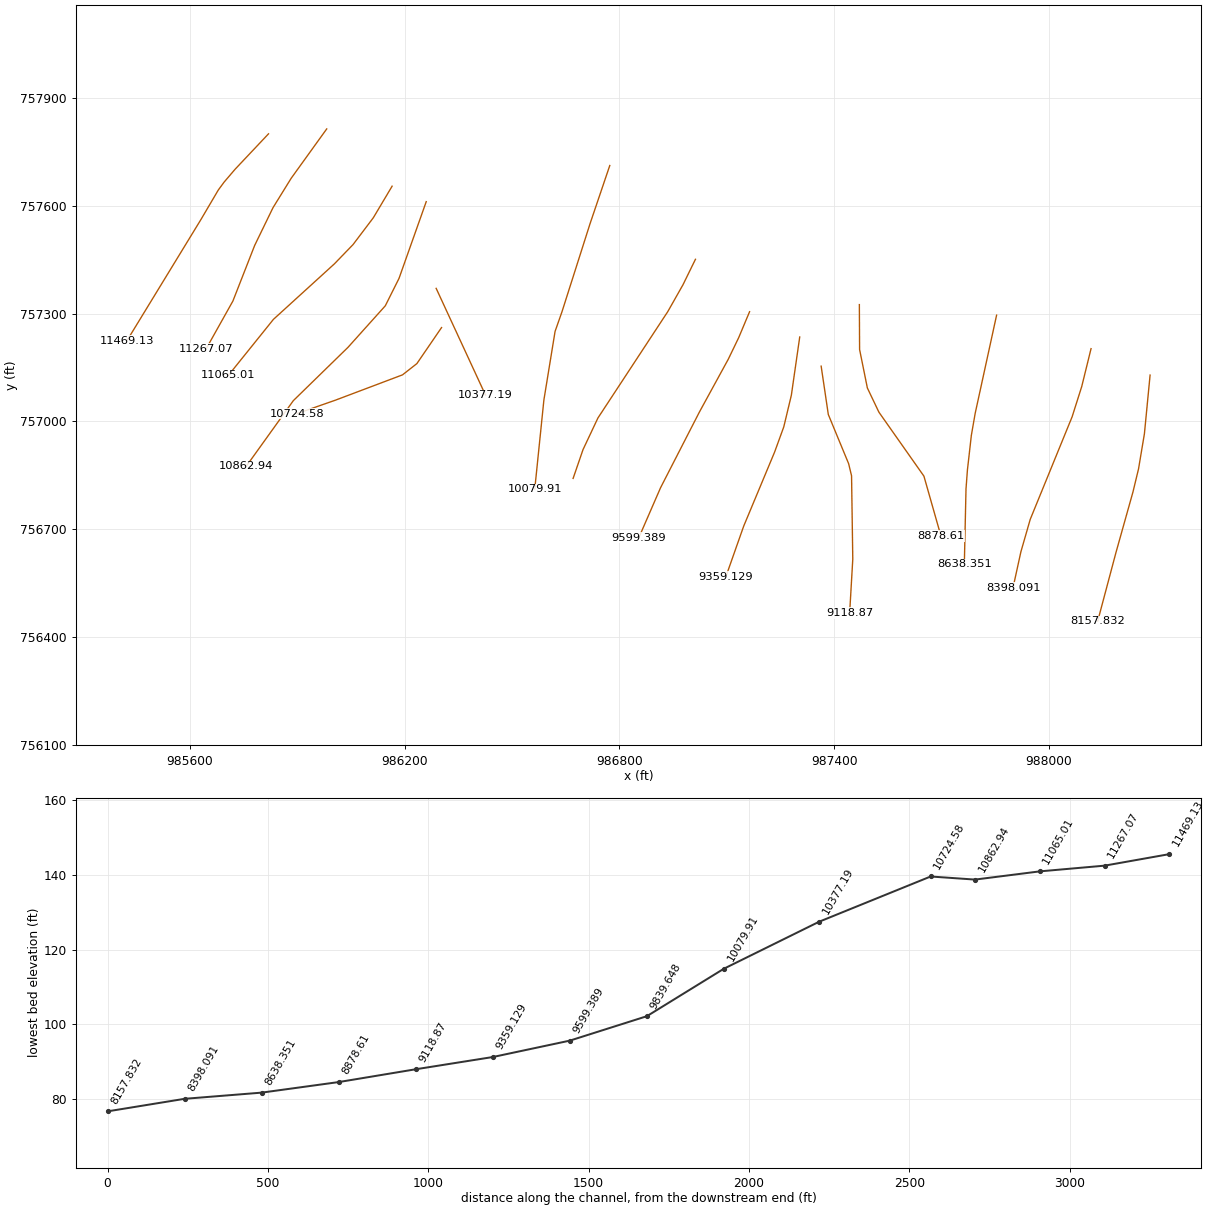
HEC-RAS study 61_ras.prj: 61

--- 61_ras.g01 (geometry) --- (continued)

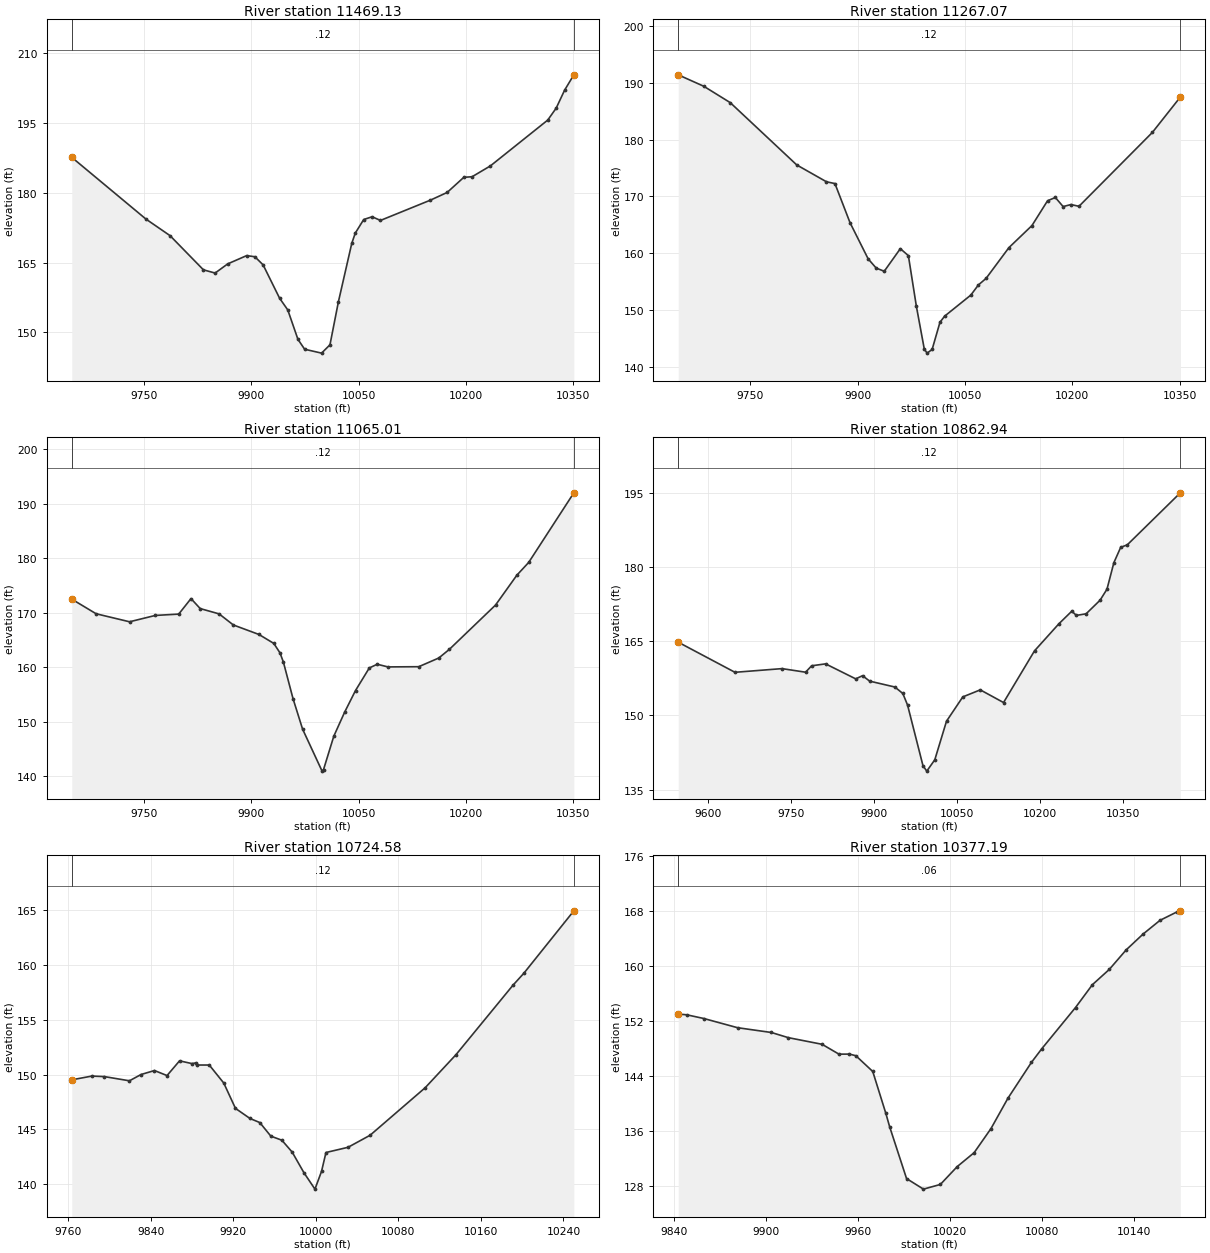
Type RM Length L Ch R = 1 ,11469.13,202.062400,202.062400,202.062400
XS GIS Cut Line= 6
985819.443442268757800.317101507985725.952605932757701.627835755
985695.620203274757666.232800581985679.242499044757644.096318916
 985630.77638767757562.068154563985423.491596845757224.009020147
#Sta/Elev= 30
9649.032187.5943 9752.78174.32759786.438170.77149833.122163.42519849.444162.7372
9867.062164.7071 9893.55166.48259905.059166.23949916.558164.48949939.556 157.342
9951.054154.80649965.245148.49319974.612 146.3699998.265145.534810010.02147.3209
10021.82156.569610040.53169.132210045.42171.323310057.21174.240510068.98174.8286
10080.63174.040410150.53178.404910173.83180.048210197.13183.299610208.78183.4313
10234.34185.757610314.52195.604310326.29198.163810338.06202.021110350.99205.3209
#Mann= 3 , 0 , 0
9649.032    0.12       09649.032    0.12       010350.99    0.12       0
#XS Ineff= 2 , 0
       0                               0
Bank Sta=9649.032,10350.99
Exp/Cntr=0.3,0.1

Type RM Length L Ch R = 1 ,11267.07,202.062300,202.062300,202.062300
XS GIS Cut Line= 6
 985982.05034384 757813.92590338985882.680778801 757676.43438411
985831.969507987757594.711505866985780.891382834757489.970550557
 985719.87160154757334.755373586985645.059983615757201.740105195
#Sta/Elev= 30
9649.025191.36869684.715189.3609 9721.73 186.4819814.707175.53129856.289172.5682
9868.114 172.2559889.202165.37919914.539159.02079925.796157.40069937.042156.8426
9959.534160.8154 9970.78159.58449981.969150.6732 9993.02143.17119996.949142.4539
10003.97143.097810014.95147.883410021.48148.954510058.06152.653210068.72154.4445
10079.38155.586810111.36161.000610143.54164.874310165.33169.231110176.23  169.81
10187.12168.212610198.02168.5655 10209.3168.2632 10311.9181.247410350.95187.4551
#Mann= 3 , 0 , 0
9649.025    0.12       09649.025    0.12       010350.95    0.12       0
#XS Ineff= 2 , 0
       0                               0
Bank Sta=9649.025,10350.95
Exp/Cntr=0.3,0.1

Type RM Length L Ch R = 1 ,11065.01,202.062400,202.062400,202.062400
XS GIS Cut Line= 6
986164.854523382757654.591792612 986112.33116588 757566.67630621
986055.620399888 757491.98722023986003.514611448757438.316851567
985833.158995396757283.842465064985707.078541193757127.716987862
#Sta/Elev= 30
9649.057172.48319683.084169.80159729.863168.32989765.777169.49389798.564169.7388
 9815.74172.58529828.594170.7547 9855.06169.77739874.924167.7461 9910.81165.9988
 9931.53164.35749940.139162.62629944.926  160.939958.321154.25229971.717148.6419
    9999140.9252   10001141.196610015.41147.344510030.58151.757610045.75155.7197
10065.02159.8576 10076.1160.537610091.07 160.04810134.13 160.08710162.12161.6796
10177.05163.282510241.48171.398410271.29176.876610287.92179.235410350.97191.9929
#Mann= 3 , 0 , 0
9649.057    0.12       09649.057    0.12       010350.97    0.12       0
#XS Ineff= 2 , 0
       0                               0
Bank Sta=9649.057,10350.97
Exp/Cntr=0.3,0.1

Type RM Length L Ch R = 1 ,10862.94,138.361500,138.361500,138.361500
XS GIS Cut Line= 6
986260.178736517757611.484984401 986184.07546705757397.747974439
986145.784991427757321.562229982 986041.37224324757205.809350277
 985888.78598421757057.574831172985757.351433584756875.106725437
#Sta/Elev= 30
 9546.85164.81359649.268158.72389734.188159.46829776.728158.74349787.633160.0424
9812.831160.43039867.205157.39679879.542158.03619892.441156.9354 9937.89155.7458
9952.285154.43529960.829152.08279988.634139.82869995.469138.730510009.95141.0221
 10031.1148.830610060.52153.747510092.08155.171510134.06152.605410189.94163.0628
10234.01168.545710257.24171.085710265.53170.236210283.12170.559410308.31173.3082
10320.75175.530210333.19180.896410345.51183.999210357.49184.519510453.14195.0323
#Mann= 3 , 0 , 0
 9546.85    0.12       0 9546.85    0.12       010453.14    0.12       0
#XS Ineff= 2 , 0
       0                               0
Bank Sta=9546.85,10453.14
Exp/Cntr=0.3,0.1

Type RM Length L Ch R = 1 ,10724.58,347.397400,347.397400,347.397400
XS GIS Cut Line= 5
  986303.0155285757261.047562763986234.053966522757160.739836231
986193.930875927757129.393671721986007.107735306757059.178263173
985899.276929319757021.562865734
#Sta/Elev= 30
9763.648149.51549783.122149.85759795.257149.80959819.528149.4268 9830.75150.0005
9843.799150.36179855.934 149.9049868.069151.24539880.205150.99279883.705151.0581
9885.374150.86369896.864150.86429910.941149.21739922.244146.9142 9936.29145.9958
9945.831145.62079956.514144.38379967.197144.01299977.203142.92929988.563 141.054
9999.246139.556110005.63141.174110009.93142.892810031.29143.367510052.66144.4639
10106.08 148.79810135.87151.804710191.06158.132310201.65159.228210250.08 164.915
#Mann= 3 , 0 , 0
9763.648    0.12       09763.648    0.12       010250.08    0.12       0
#XS Ineff= 2 , 0
       0                               0
Bank Sta=9763.648,10250.08
Exp/Cntr=0.3,0.1

Type RM Length L Ch R = 1 ,10377.19,297.278100,297.278100,297.278100
XS GIS Cut Line= 2
986287.969369531757370.132215306986425.892493457757072.970575526
#Sta/Elev= 30
 9842.45  152.999848.108152.87619859.133152.34039881.182 150.9999903.231150.3017
9914.256 149.5519936.305148.5821 9947.33 147.1459954.162147.15369958.354146.9158
9969.379144.62059977.915138.51629980.404136.56219991.428129.016910002.45127.4779
10013.48128.1591 10024.5130.763910035.53132.789910046.55 136.31210057.58140.7243
10072.93145.948810079.63147.922210101.67153.9372 10112.7157.268210123.72159.4918
10134.75162.343710145.77164.6443 10156.8166.643110167.82167.866210170.06168.0299
#Mann= 3 , 0 , 0
 9842.45    0.06       0 9842.45    0.06       010170.06    0.06       0
#XS Ineff= 2 , 0
       0                               0
Bank Sta=9842.45,10170.06
Exp/Cntr=0.3,0.1

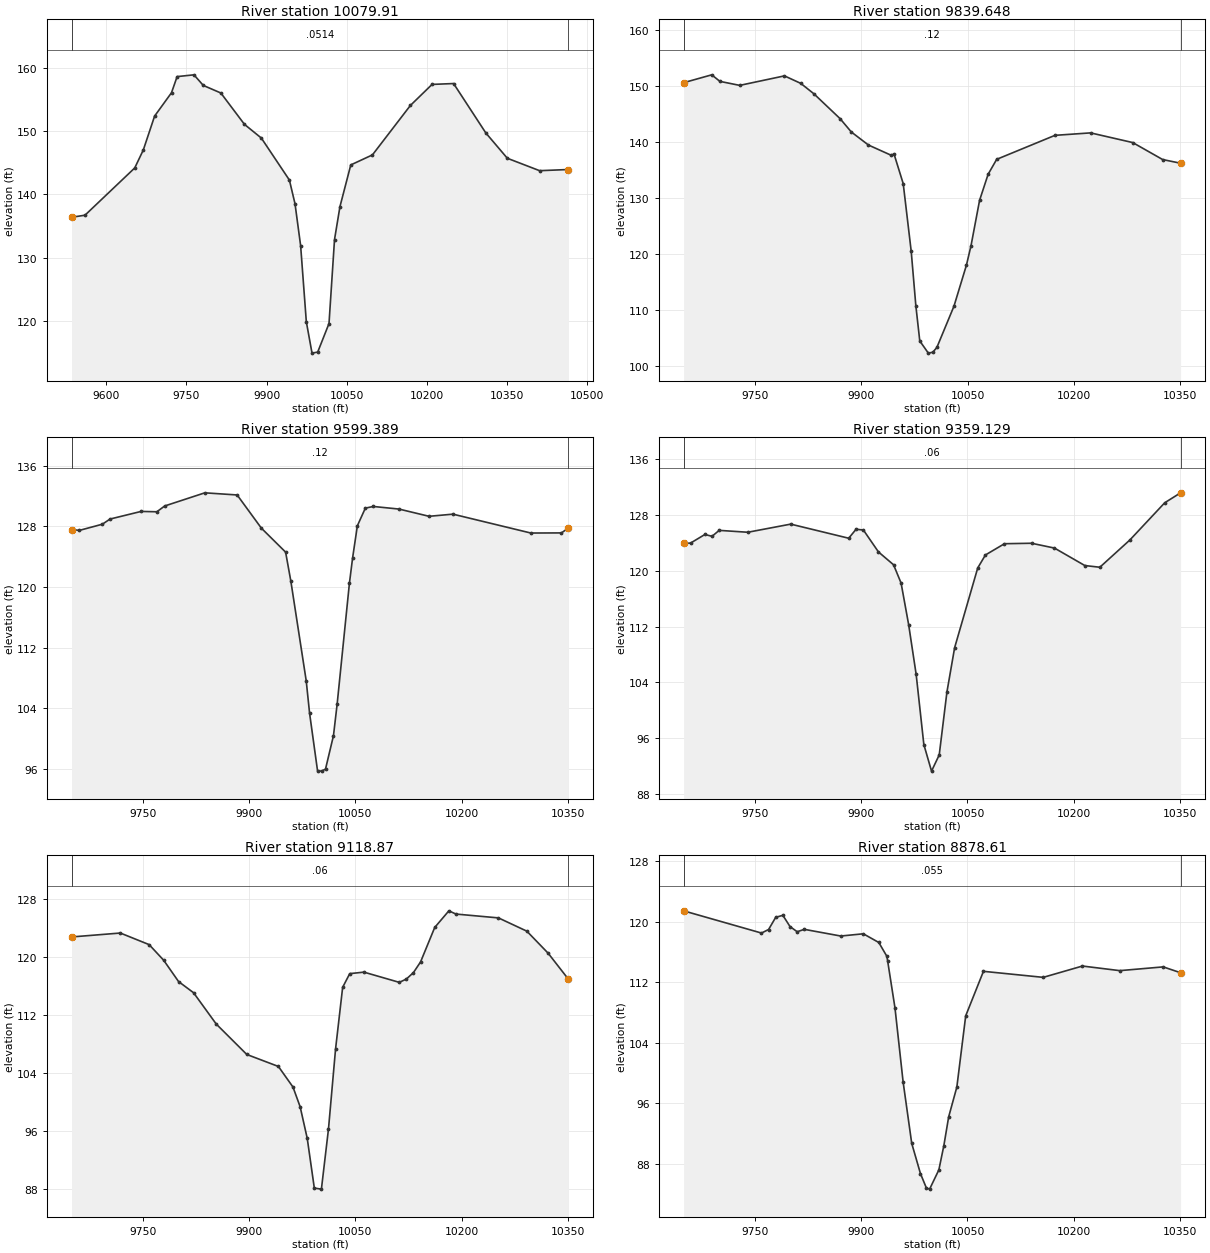
Type RM Length L Ch R = 1 ,10079.91,240.259500,240.259500,240.259500
XS GIS Cut Line= 6
986773.128066312757712.093696156986718.051376345757550.405930392
986639.387711289757304.562691243986620.237120748757250.294269795
 986588.98361277757059.380691079986563.460336277756811.273819872
#Sta/Elev= 30
9535.284136.38169560.491136.70979653.531144.18119669.548147.02459690.677152.3776
 9722.27156.07039732.769158.61779764.268158.89939781.734157.22349814.547156.0272
9858.763151.06479890.261148.90559942.758142.26299953.258 138.5119963.757131.8907
9974.395119.8736 9985.04114.90769995.684115.074410016.81119.585710027.13132.8649
10037.27 138.06110057.53144.656510098.07 146.245   10169154.056910209.53157.3849
10249.79157.5217 10310.1149.709710350.31145.709910410.63 143.74710464.64143.9312
#Mann= 3 , 0 , 0
9535.284  0.0514       09535.284  0.0514       010464.64  0.0514       0
#XS Ineff= 2 , 0
       0                               0
Bank Sta=9535.284,10464.64
Exp/Cntr=0.3,0.1

Type RM Length L Ch R = 1 ,9839.648,240.259500,240.259500,240.259500
XS GIS Cut Line= 6
 987012.54030167757451.023281775986977.528299048757379.919500844
986935.238552026757305.458118184986739.928252424757009.215537714
986698.436809074756921.521651621986670.637228359756841.138518784
#Sta/Elev= 30
9649.036150.53369688.742151.94179700.336150.77059728.293150.05649791.451151.7538
9814.469150.41749832.908148.5684 9869.99 144.1189885.948141.7245 9910.11139.3963
9941.381 137.6169946.352137.74439959.204132.50099970.514120.38939977.027110.7022
9982.595 104.3929994.676102.2142   10001102.375410006.73103.225910030.87110.5956
10048.47117.9209   10055121.432610067.07129.523410079.14134.178510091.21136.8405
10173.54141.128810223.87141.568210283.36139.838410325.69136.800310350.93 136.148
#Mann= 3 , 0 , 0
9649.036    0.12       09649.036    0.12       010350.93    0.12       0
#XS Ineff= 2 , 0
       0                               0
Bank Sta=9649.036,10350.93
Exp/Cntr=0.3,0.1

Type RM Length L Ch R = 1 ,9599.389,240.259500,240.259500,240.259500
XS GIS Cut Line= 6
987163.785231584757305.176821007987133.361743092757232.925428637
987104.237583368757172.864909476987023.417934697757025.595507245
986915.120963153756815.366923219986854.170927223756675.788949926
#Sta/Elev= 30
9649.025127.59649660.067127.48119692.618128.29899703.469128.98019747.342 129.987
 9769.57129.94149780.683130.70759837.362132.44379882.989132.1605 9917.21127.7755
9951.431124.6115 9958.87120.75759980.568107.60219985.317103.31539996.56195.71575
10002.4695.68383 10007.8  95.95710019.05100.373710024.29104.588910041.55120.4875
10046.12123.8838 10052.8128.094110064.05130.4204 10075.3130.6419 10111.6130.2992
10154.05129.3427 10187.8129.625910297.84127.132510341.04127.149310350.98127.8021
#Mann= 3 , 0 , 0
9649.025    0.12       09649.025    0.12       010350.98    0.12       0
#XS Ineff= 2 , 0
       0                               0
Bank Sta=9649.025,10350.98
Exp/Cntr=0.3,0.1

Type RM Length L Ch R = 1 ,9359.129,240.259500,240.259500,240.259500
XS GIS Cut Line= 6
987303.936564505757234.743125407987280.539097065757072.649031477
987259.365051527 756984.56642279987233.696345389756914.367525045
 987147.27856495 756708.08219166987097.535128768756567.515928327
#Sta/Elev= 30
9649.042123.88929658.886123.94849679.093125.17649689.197124.9186  9699.3125.7666
9739.715125.49629800.337126.66039882.255124.64049892.632125.9273 9903.01125.8134
9924.293122.67469945.588120.84159956.236118.22039966.883112.28229977.531105.1379
9988.36695.109619999.214 91.2992 10010.193.6205210020.97102.621210031.85108.9705
10064.48120.386310075.36122.245510102.25123.855710140.54123.921910172.87123.2323
10215.75120.730410236.96120.486610279.39124.3921 10328.6129.717110350.98131.1411
#Mann= 3 , 0 , 0
9649.042    0.06       09649.042    0.06       010350.98    0.06       0
#XS Ineff= 2 , 0
       0                               0
Bank Sta=9649.042,10350.98
Exp/Cntr=0.3,0.1

Type RM Length L Ch R = 1 , 9118.87,240.259500,240.259500,240.259500
XS GIS Cut Line= 6
987363.820028651757153.622950166987383.824428933757018.977171012
987440.579027911756882.215655751 987448.76845778756848.456427721
987452.204737853756616.522858622987443.456614115 756466.38507456
#Sta/Elev= 30
9649.145122.77699718.085123.31739758.767121.72089779.337119.5645 9800.33116.6308
9821.505115.09229853.574110.77379896.686106.58499941.335104.93199961.924102.0938
9972.03799.376899982.046 95.02579992.05588.1723410002.0688.0307810012.0696.32084
10022.06107.349410032.07115.838110042.07117.722210062.07117.930310112.08116.5214
10122.08116.979310132.08117.873410142.08 119.33410162.08124.083110182.08126.3771
10192.08125.931310252.11125.4025 10292.2123.573710322.28120.536110350.98116.9424
#Mann= 3 , 0 , 0
9649.145    0.06       09649.145    0.06       010350.98    0.06       0
#XS Ineff= 2 , 0
       0                               0
Bank Sta=9649.145,10350.98
Exp/Cntr=0.3,0.1

Type RM Length L Ch R = 1 , 8878.61,240.259500,240.259500,240.259500
XS GIS Cut Line= 6
987470.578102555757324.914865177987471.242811786757199.969763593
987492.946431551757092.902758208987525.222451586757025.478953143
987651.030395338756847.419374669987698.569676359756680.847526769
#Sta/Elev= 30
9649.143121.45519759.128118.51219769.142118.98229779.199120.59489789.299120.8614
9799.399119.37179809.499118.68699819.599119.00289871.101118.11789902.952118.4134
9924.794117.26259936.213115.42539937.333114.78499947.633108.60039959.088 98.8258
9971.26290.672289983.57586.673689991.95884.759379996.52984.60735 10009.687.15648
10016.6290.3533610023.45 94.175410034.9998.1217710047.51107.554210072.56113.4447
10156.98112.646710212.35114.145510265.07113.535110326.42114.032510350.92113.2581
#Mann= 3 , 0 , 0
9649.143   0.055       09649.143   0.055       010350.92   0.055       0
#XS Ineff= 2 , 0
       0                               0
Bank Sta=9649.143,10350.92
Exp/Cntr=0.3,0.1

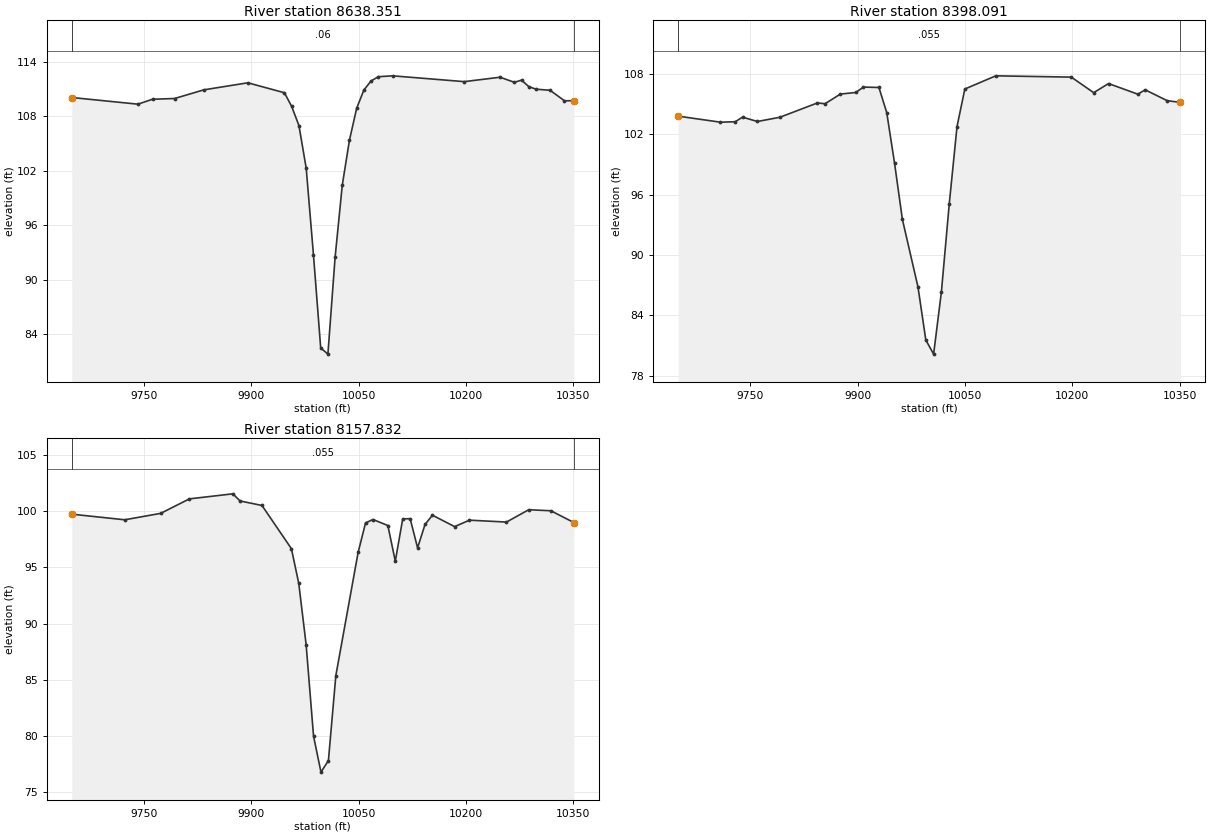
Type RM Length L Ch R = 1 ,8638.351,240.259500,240.259500,240.259500
XS GIS Cut Line= 6
987854.113629949 757295.56738164987794.263885684757022.312826145
 987783.55679291756961.022305859987772.599138084756864.755568017
987768.605067353756811.874411156 987763.93806649756601.846720154
#Sta/Elev= 30
9649.019110.0853 9741.51109.35039761.943109.89519792.705109.97389833.722110.9319
9895.246111.70729946.338110.6092 9956.49109.09519966.641106.98739976.793102.2839
9986.94492.71588 9997.0582.4731110007.1281.7847410017.18 92.448310027.24100.4291
10037.31105.402510047.37108.903110057.43110.9135 10067.5111.910210077.56 112.379
10097.65112.476610197.79111.8358 10247.8112.321510267.81111.762710277.81111.9996
10287.81111.299110297.82111.006510317.82  110.8810337.83109.725710350.98109.7288
#Mann= 3 , 0 , 0
9649.019    0.06       09649.019    0.06       010350.98    0.06       0
#XS Ineff= 2 , 0
       0                               0
Bank Sta=9649.019,10350.98
Exp/Cntr=0.3,0.1

Type RM Length L Ch R = 1 ,8398.091,240.259500,240.259500,240.259500
XS GIS Cut Line= 6
988118.062641828757202.338415506988092.059556165757097.089288217
988065.127700925757012.552836811 987948.04499173756727.015549759
987921.986646572756636.768299142987900.054467869756537.017366807
#Sta/Elev= 30
9649.044103.81419708.107103.21379728.708103.25989739.009103.71649759.651103.2829
9791.136 103.7049843.612105.1296 9854.29105.05119875.764106.01349897.238106.1693
9907.975106.70869929.614106.66889940.538104.16459951.46399.129239962.38793.55062
9984.23686.805599995.16181.5355410006.0880.1316910016.9886.3407610027.8895.04089
10038.78 102.77310049.68106.5142   10093 107.82810198.61107.699110229.84106.1523
10250.63107.058310291.58105.999610301.82106.436510332.54105.357810350.95105.1835
#Mann= 3 , 0 , 0
9649.044   0.055       09649.044   0.055       010350.95   0.055       0
#XS Ineff= 2 , 0
       0                               0
Bank Sta=9649.044,10350.95
Exp/Cntr=0.3,0.1

Type RM Length L Ch R = 1 ,8157.832,240.259500,240.259500,240.259500
XS GIS Cut Line= 6
988283.039045466757128.694832029988267.194244213756965.463017923
988250.774540724 756867.74474942988235.236362782756803.530104434
988187.853355452756635.473282875988136.706468816756444.003060104
#Sta/Elev= 30
9649.02899.737879723.06999.238479773.30499.809039813.495   101.1 9874.23101.5488
9884.405100.9122 9914.96100.51269956.11596.665949966.40393.571129976.69288.12719
9987.06279.980119997.44676.7777610007.85 77.802510018.2485.3729710049.4196.33902
 10059.898.9603610070.1999.2621310090.9798.7292110101.3695.5497810111.7599.31928
10122.1499.3362110132.53 96.740410142.92 98.8216 10153.399.6446810184.3698.63023
10205.0699.2037610256.8199.0357310287.86 100.13110318.91 100.042   1035198.99254
#Mann= 3 , 0 , 0
9649.028   0.055       09649.028   0.055       0   10351   0.055       0
#XS Ineff= 2 , 0
       0                               0
Bank Sta=9649.028,10351
Exp/Cntr=0.3,0.1