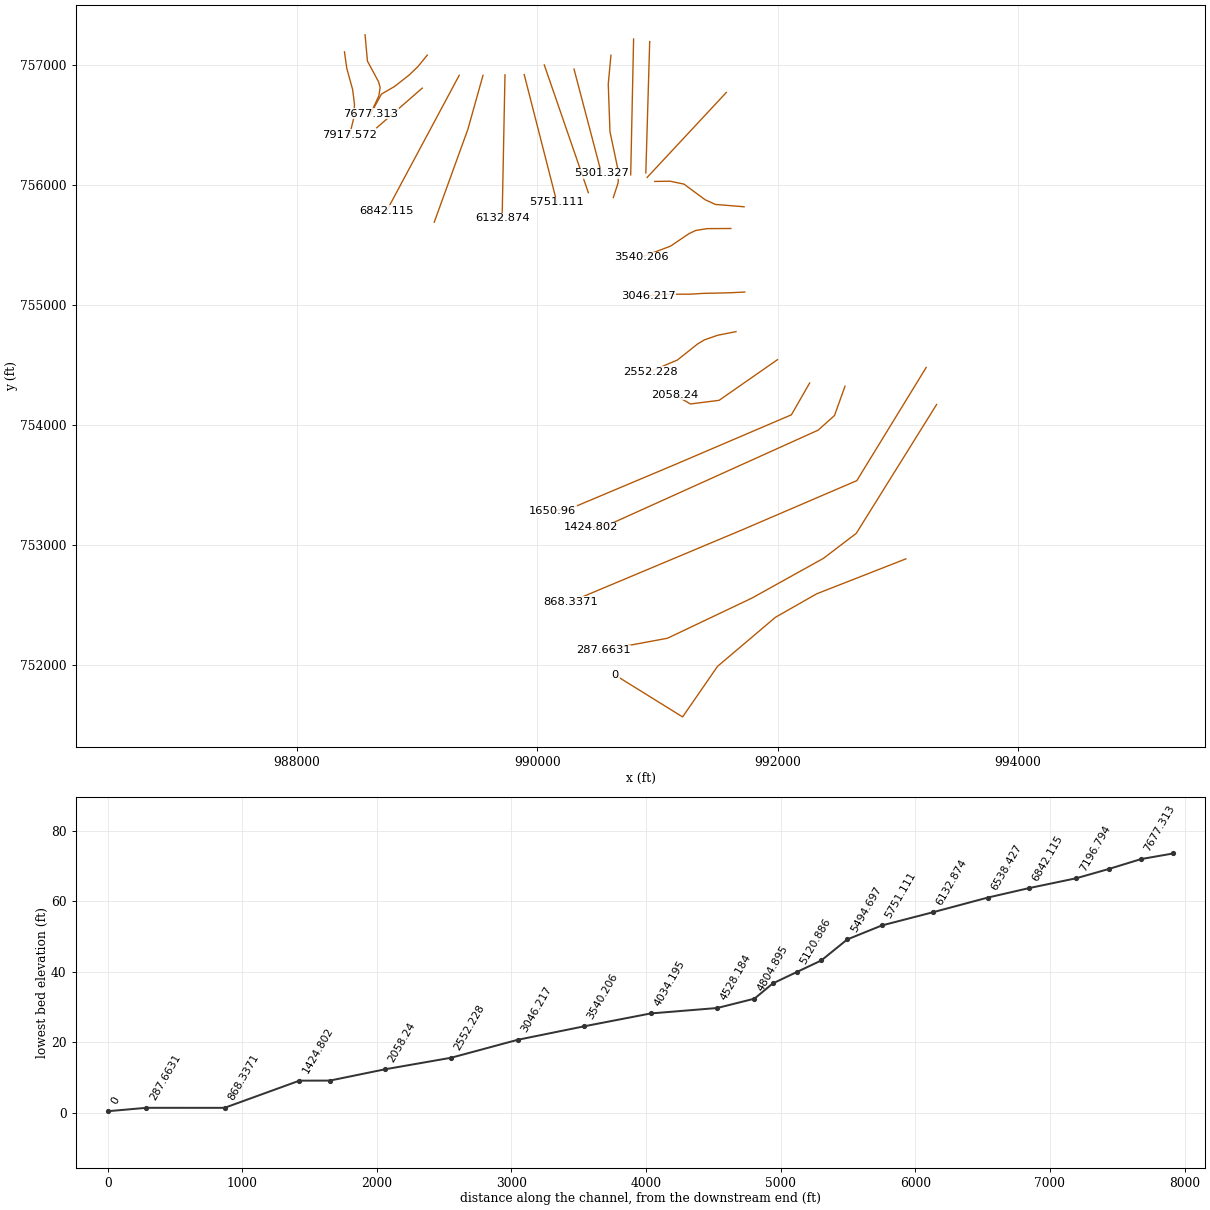
HEC-RAS study 61_ras.prj: 61

--- 61_ras.g01 (geometry) --- (continued)

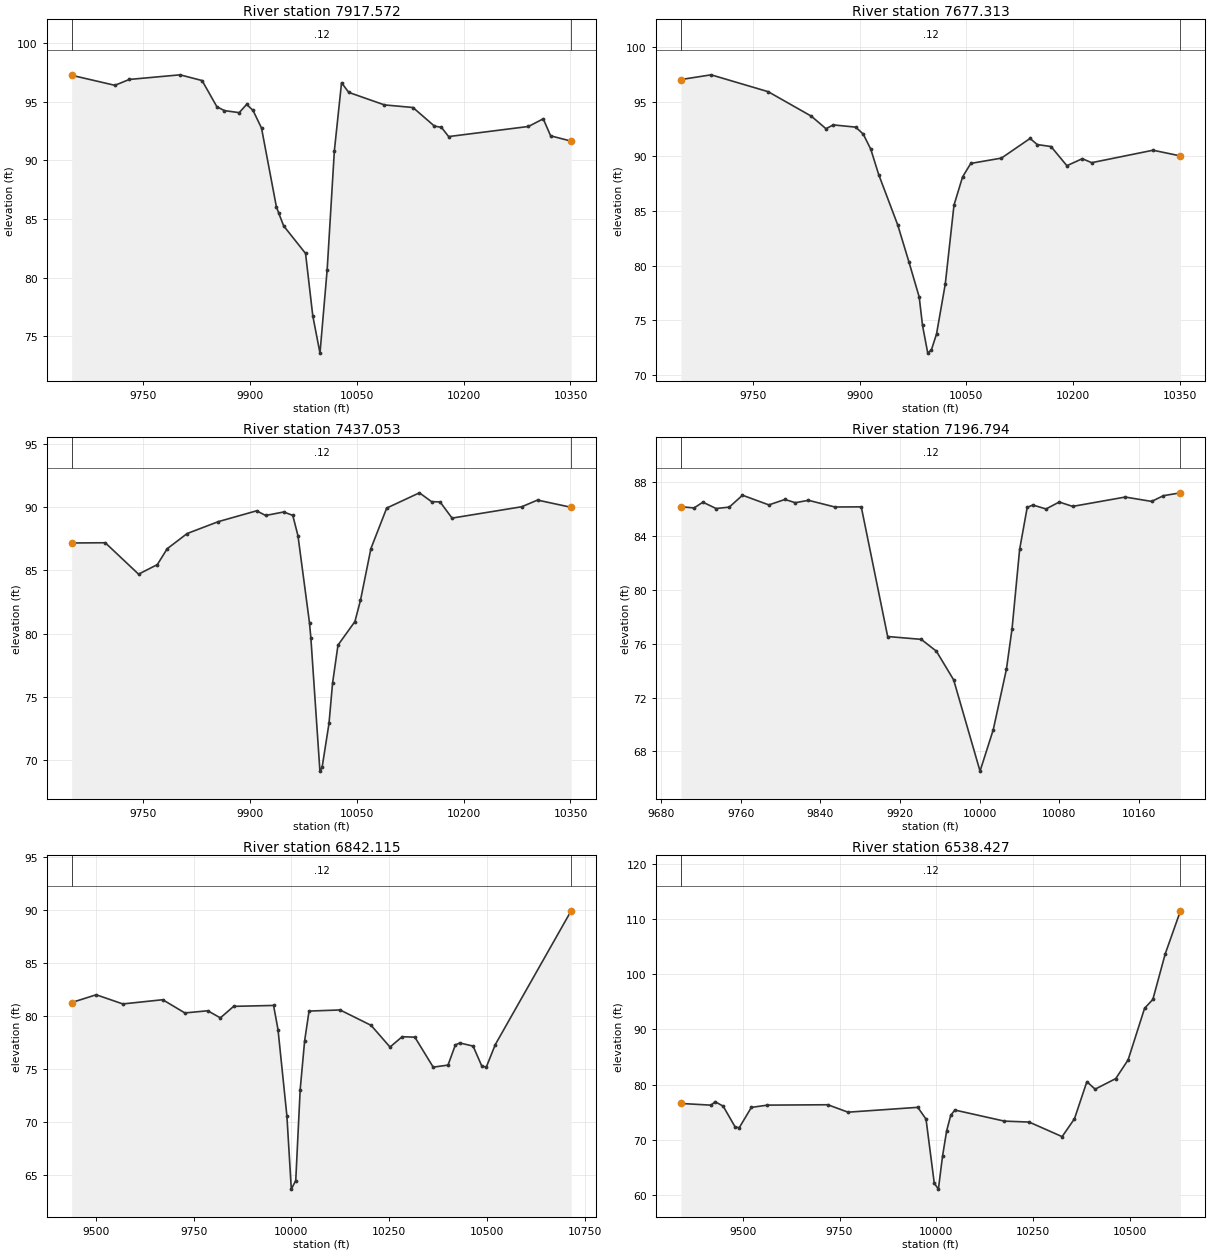
Type RM Length L Ch R = 1 ,7917.572,240.259500,240.259500,240.259500
XS GIS Cut Line= 6
988394.340645848757105.477849833988413.219899381756969.585779358
 988462.25580285756791.309069893 988477.77290436756667.710665083
988472.675614085756559.436492239988438.171877164756417.245705533
#Sta/Elev= 30
9649.057 97.26619709.81996.410089730.11796.910729801.39697.304119832.32696.81611
9853.19794.57896 9863.6494.254219884.52794.07981 9894.9794.784959903.95594.26656
9915.85792.764829936.69686.072769939.86685.538239946.97384.424679977.72282.07807
9987.86976.768769998.01673.5765610008.1380.7050910018.22 90.830910028.3296.63082
10038.3895.8081410088.6294.7388810128.6694.5183510158.6892.9401110168.7492.82157
10178.7992.0394710290.9592.9013310311.7293.55205 10322.192.1044410350.9191.65068
#Mann= 3 , 0 , 0
9649.057    0.12       09649.057    0.12       010350.91    0.12       0
#XS Ineff= 2 , 0
       0                               0
Bank Sta=9649.057,10350.91
Exp/Cntr=0.3,0.1

Type RM Length L Ch R = 1 ,7677.313,240.259500,240.259500,240.259500
XS GIS Cut Line= 6
988565.792670891 757247.35646876988585.358338133757029.195275484
988678.061974902756856.398961036988691.153206761756808.086819285
988680.103956657756738.898776247988611.587793813 756590.18252312
#Sta/Elev= 30
9649.11497.054349691.47797.485729771.62395.940899832.35793.692389852.84492.54591
9863.08892.89495 9894.6392.690549905.20992.053099915.81290.665499926.88388.34761
9953.69683.717939969.28280.358369983.82477.118899988.50674.504219995.858 71.9709
   1000172.2773910008.2273.7349910020.4778.3107410032.72 85.543110044.7788.12621
10056.3289.3645210099.3489.8503810139.6291.6532610149.7191.0917110169.0390.91121
10191.3189.1533110212.9989.7966510226.1889.4315210312.3290.5732210350.8590.05058
#Mann= 3 , 0 , 0
9649.114    0.12       09649.114    0.12       010350.85    0.12       0
#XS Ineff= 2 , 0
       0                               0
Bank Sta=9649.114,10350.85
Exp/Cntr=0.3,0.1

Type RM Length L Ch R = 1 ,7437.053,240.259500,240.259500,240.259500
XS GIS Cut Line= 6
989083.587170447 757078.41952057989006.002562365756983.044053919
988931.820231203756911.954191158988810.754039156 756817.05990861
988702.163678906756754.040697473988608.446359483756582.417599351
#Sta/Elev= 30
9649.04787.160649696.27687.179019743.10684.699559769.46985.454919783.31586.70608
 9811.3387.905569855.33588.848259908.93989.699599921.65289.331549947.07789.60767
 9959.7989.337759967.08587.72818 9983.2880.854259985.21679.651179997.92869.15473
   1000169.4500610010.6972.9273210015.6776.0884810023.3179.1003910047.0680.95672
10054.9182.63465 10069.686.7234610091.7489.9162210137.7491.1186610154.8390.42006
 10166.7  90.40410183.6189.12447 10281.590.0195610303.6890.5464810350.9189.97546
#Mann= 3 , 0 , 0
9649.047    0.12       09649.047    0.12       010350.91    0.12       0
#XS Ineff= 2 , 0
       09818.802                       0
Bank Sta=9649.047,10350.91
Exp/Cntr=0.3,0.1

Type RM Length L Ch R = 1 ,7196.794,354.679100,354.679100,354.679100
XS GIS Cut Line= 2
989041.629721493756803.669402122988663.157499313756473.808291018
#Sta/Elev= 30
9699.91786.160339713.11186.072689721.97686.500839735.24186.029549748.50686.13384
9761.77187.016929788.30186.297829804.43186.701489814.83286.461369828.09786.63853
9854.62786.143049881.15786.152889907.68776.52982 9941.4176.31931 9956.6375.44355
9974.01273.3127410000.5466.5394210013.8169.6097710027.0774.1078610032.7377.11911
10040.3482.9998810047.9586.11382 10053.686.2894410066.8785.9965810080.1386.51231
10093.6186.1869810146.46 86.880710172.9986.5567810184.9386.9832710201.9687.19407
#Mann= 3 , 0 , 0
9699.917    0.12       09699.917    0.12       010201.96    0.12       0
#XS Ineff= 2 , 0
       0                10167.99       0
Bank Sta=9699.917,10201.96
Exp/Cntr=0.3,0.1

Type RM Length L Ch R = 1 ,6842.115,303.687500,303.687500,303.687500
XS GIS Cut Line= 2
989349.300158441756910.432965323988746.385884553755783.935242951
#Sta/Elev= 30
9437.90481.294859500.77782.02924 9568.8381.16384 9670.9181.561119727.62180.31545
9786.08880.520359818.35879.850799852.38580.936829954.464 81.02179965.80678.74251
9988.49170.629799999.83363.7099910011.1864.5211310022.5273.0859910033.8677.67475
 10045.280.49231 10124.680.5958310203.99 79.144310252.3177.0996410283.3978.07534
10315.8978.0311610362.78 75.207810400.66 75.400110419.4977.2992110430.8477.48753
10464.8677.1913410487.5575.2683810498.8975.2395410521.5777.32935 10715.689.93952
#Mann= 3 , 0 , 0
9437.904    0.12       09437.904    0.12       0 10715.6    0.12       0
#XS Ineff= 2 , 0
       09772.845        10099.01       0
Bank Sta=9437.904,10715.6
Exp/Cntr=0.3,0.1

Type RM Length L Ch R = 1 ,6538.427,405.552800,405.552800,405.552800
XS GIS Cut Line= 3
 989547.13126266756909.872707605989421.263207108756460.653957605
989141.315290511755688.084513173
#Sta/Elev= 30
9341.03376.564239418.78976.259669429.17476.889749449.94576.07094  9481.172.27386
9491.48572.188829522.64175.855069564.18176.264629719.95876.333029771.88474.98624
9951.83875.86416 9973.1173.729629994.38362.1088110005.0261.0456610015.66 67.0067
10026.2971.6016210036.9374.4398710047.5675.37222 10175.273.3664510239.0273.19622
10324.1170.5576310356.0273.7993810387.93 80.5124 10409.279.1557310462.3881.06809
10494.29 84.460310536.8393.8149210558.1195.4137410590.01103.661510629.28111.4662
#Mann= 3 , 0 , 0
9341.033    0.12       09341.033    0.12       010629.28    0.12       0
#XS Ineff= 2 , 0
       09882.385        10087.56       0
Bank Sta=9341.033,10629.28
Exp/Cntr=0.3,0.1

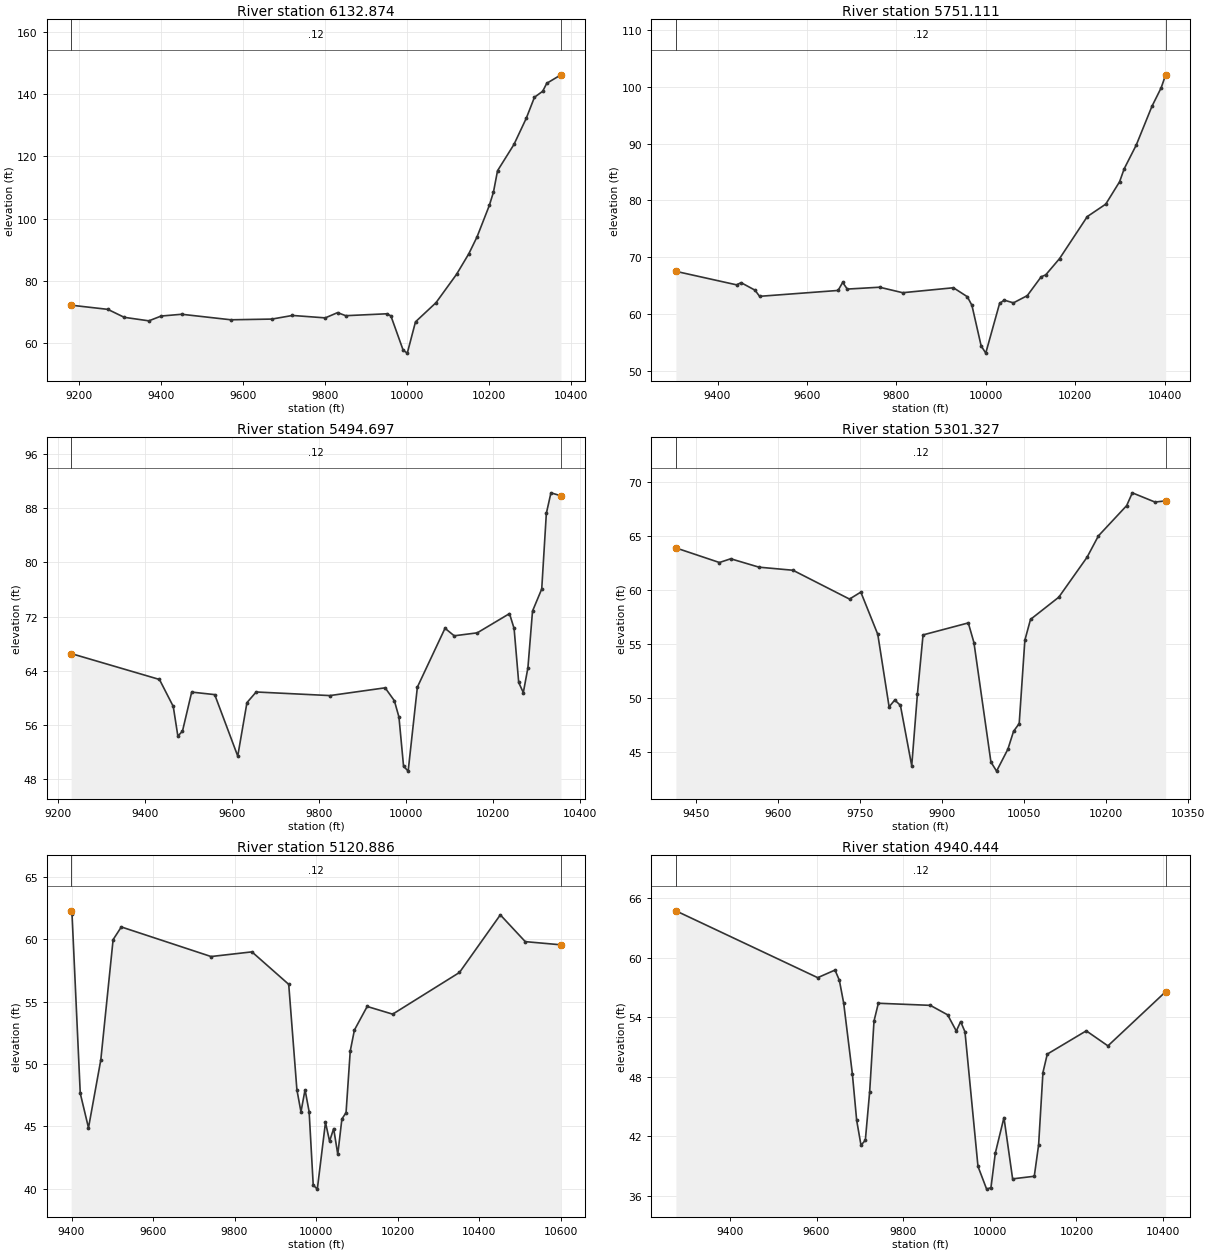
Type RM Length L Ch R = 1 ,6132.874,381.763700,381.763700,381.763700
XS GIS Cut Line= 2
989730.088120937756914.399506584989706.288873285 755720.47058256
#Sta/Elev= 30
9180.33372.27796 9269.7570.940979309.75868.38779 9369.7767.257419399.776 68.7984
9449.78669.36742 9569.8167.59531 9669.8367.82226 9719.8468.985299799.85668.20852
9829.86269.889789849.86668.910599949.885 69.52069959.88768.851669989.89357.81675
9999.89556.90357 10019.966.9405610069.9173.0848710119.9282.1697810149.9388.78479
10169.9394.1774610199.94104.280910209.94108.527910219.94115.408910259.95123.8261
10289.95132.222110309.96138.970910329.96140.882510339.96143.4454 10374.5146.1582
#Mann= 3 , 0 , 0
9180.333    0.12       09180.333    0.12       0 10374.5    0.12       0
#XS Ineff= 2 , 0
       09869.894                       0
Bank Sta=9180.333,10374.5
Exp/Cntr=0.3,0.1

Type RM Length L Ch R = 1 ,5751.111,256.414100,256.414100,256.414100
XS GIS Cut Line= 2
989890.013207108756916.383124262990161.280568272755855.185207605
#Sta/Elev= 30
9306.87967.518989442.48765.144399452.80965.523479483.77364.205629494.09563.12354
9669.56164.157479679.88365.567039690.20464.398969762.45564.725259814.06363.75952
  9927.664.630979958.56463.058199968.88661.550469989.52954.415439999.85153.13382
10030.8261.8817610041.1462.4504510061.78 61.976610092.7463.2459410123.71 66.5505
10134.0366.90374   1016569.7689310226.9277.1492410268.2179.3393310299.1883.28056
 10309.585.5663510336.4689.7351110371.4396.5286310392.0799.78712 10402.2 102.079
#Mann= 3 , 0 , 0
9306.879    0.12       09306.879    0.12       0 10402.2    0.12       0
#XS Ineff= 2 , 0
       09878.811                       0
Bank Sta=9306.879,10402.2
Exp/Cntr=0.3,0.1

Type RM Length L Ch R = 1 ,5494.697,193.369100,193.369100,193.369100
XS GIS Cut Line= 2
990057.113901585756996.678263143990423.867373794755933.310207605
#Sta/Elev= 30
9231.35166.531979434.10962.708519465.84358.725959476.42254.34806    948755.07337
9508.15660.844529561.04660.471579613.93651.397659635.09359.288859656.24960.86094
9825.49860.329289952.43461.474999973.591  59.5779984.16957.161339994.74749.89639
10005.3249.1744610026.4861.5786810089.9570.2646710111.1169.15533   1016469.59368
10238.0472.4318510248.6270.23451 10259.262.2606810269.7860.7698610280.3564.43127
10290.9372.8102410312.0976.0702710322.6787.2273210333.2490.2661510356.1989.82233
#Mann= 3 , 0 , 0
9231.351    0.12       09231.351    0.12       010356.19    0.12       0
#XS Ineff= 2 , 0
       09855.568                       0
Bank Sta=9231.351,10356.19
Exp/Cntr=0.3,0.1

Type RM Length L Ch R = 1 ,5301.327,180.441900,180.441900,180.441900
XS GIS Cut Line= 2
990304.509734899756961.956040934990532.374318242756096.070624277
#Sta/Elev= 30
9413.39963.902639492.97562.549719513.656  62.8969565.35862.116829627.40161.83189
9730.80659.157849751.48659.804359782.50855.882439803.18949.164849813.52949.79523
 9823.8749.300199844.55143.693119854.89150.323139865.23255.834619947.95556.94704
9958.29655.118559989.31744.045089999.65843.2010210020.3445.2372310030.6846.89134
10041.0247.6173410051.3655.34364 10061.757.27393 10113.459.3337510165.1163.04174
10185.7965.0172810237.4967.8285210247.8369.0121810289.1968.1571510308.7668.26446
#Mann= 3 , 0 , 0
9413.399    0.12       09413.399    0.12       010308.76    0.12       0
#XS Ineff= 2 , 0
       09909.948                       0
Bank Sta=9413.399,10308.76
Exp/Cntr=0.3,0.1

Type RM Length L Ch R = 1 ,5120.886,180.441900,180.441900,180.441900
XS GIS Cut Line= 6
990611.647724423757077.100753679 990589.45114517756836.593415902
990603.769844194756440.844778291990677.304883279756092.282744613
990670.777122264756013.261226565990631.509946066755892.997154517
#Sta/Elev= 30
9399.06562.282179401.18862.033839421.40147.640789441.61444.871059471.85650.33006
9502.025 59.97169522.13860.989159742.38758.614969842.65358.989469932.94656.38421
9953.01247.925879963.01246.151629973.01247.926059983.018 46.16769993.07140.27378
10003.11 39.953510023.1745.3128210033.17 43.797510043.2344.8105610053.3242.74648
10063.4145.5824710073.6446.08814 10083.9 51.030410094.1652.7189210125.4354.60836
   1018853.9916810351.9457.3364210452.19 61.957410513.3759.8109310600.9359.55472
#Mann= 3 , 0 , 0
9399.065    0.12       09399.065    0.12       010600.93    0.12       0
#XS Ineff= 2 , 0
       09918.562        10130.72       0
Bank Sta=9399.065,10600.93
Exp/Cntr=0.3,0.1

Type RM Length L Ch R = 1 ,4940.444,135.548800,135.548800,135.548800
XS GIS Cut Line= 2
990800.318623751757212.356635034990776.205042005756081.697580531
#Sta/Elev= 30
9275.19564.730759602.62657.992249642.63558.757619652.63757.73357 9662.6455.42957
9682.64448.309179692.64743.604469702.64941.098989712.65141.600589722.65346.49167
9732.65653.611859742.65855.412229862.68555.200949902.69454.244519922.69952.61027
9932.70153.561759942.70352.53393 9972.7138.971919992.71536.6715510002.7236.82349
10012.7240.2921610032.7243.8842910052.7337.7067910102.7437.9687310112.7441.12494
10122.7448.4281810132.7550.2849610222.7752.6307110272.7851.1155510406.1156.57685
#Mann= 3 , 0 , 0
9275.195    0.12       09275.195    0.12       010406.11    0.12       0
#XS Ineff= 2 , 0
       09934.654         10077.9       0
Bank Sta=9275.195,10406.11
Exp/Cntr=0.3,0.1

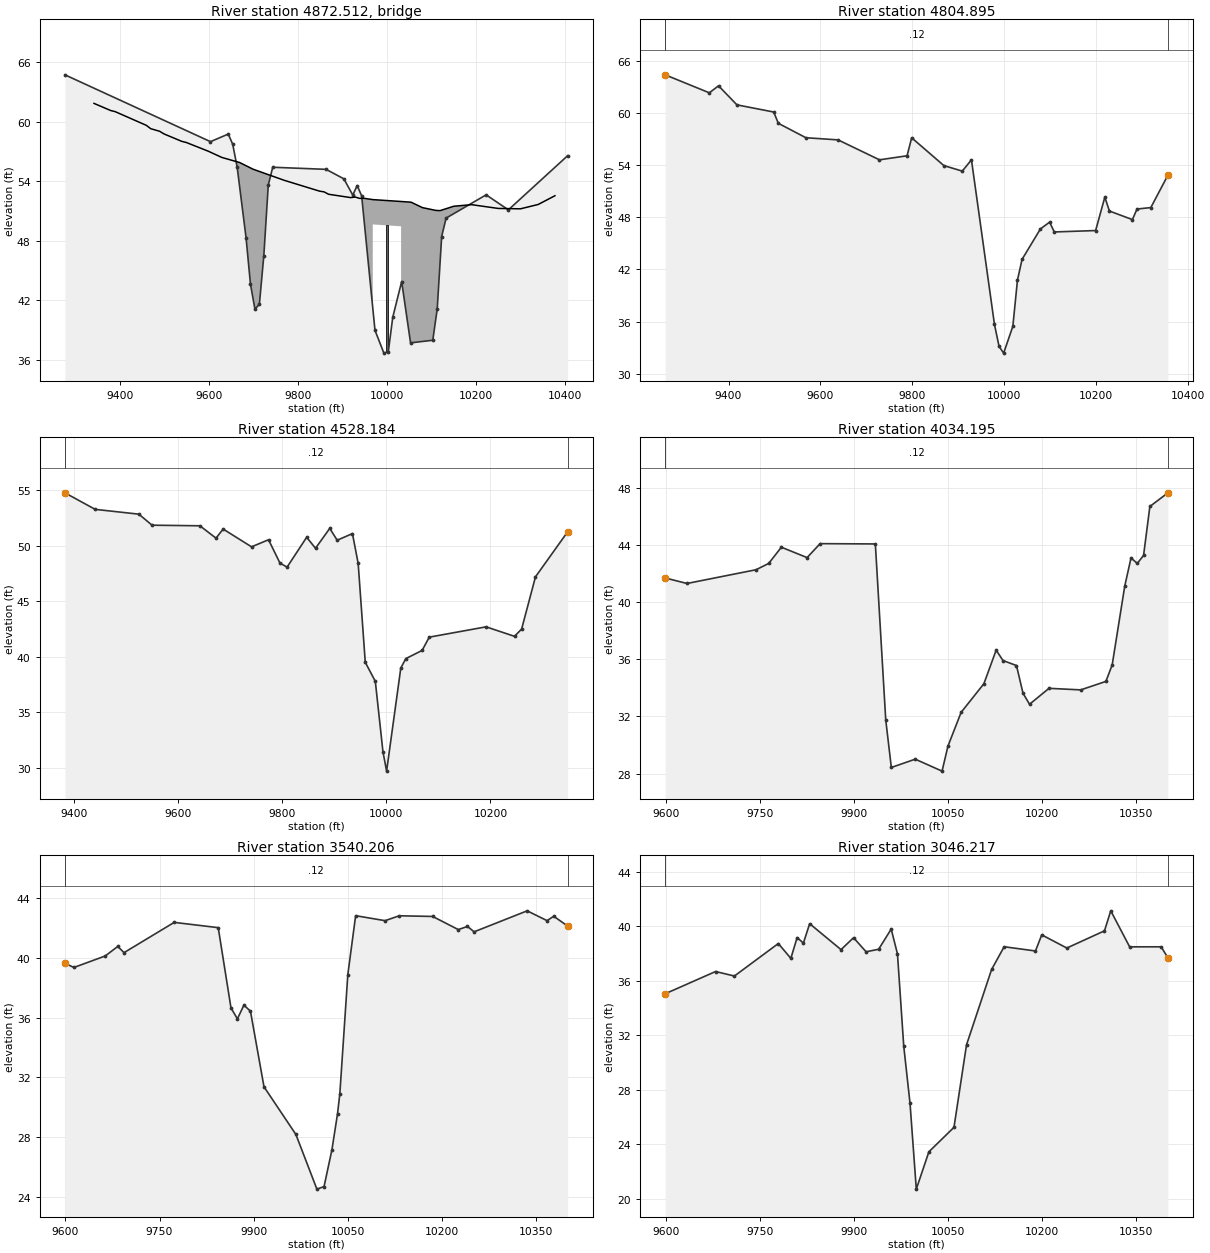
Type RM Length L Ch R = 3 ,4872.512,,,
BEGIN DESCRIPTION:
END DESCRIPTION:
Bridge Culvert--1,0,-1,-1, 0
Deck Dist Width WeirC Skew NumUp NumDn MinLoCord MaxHiCord MaxSubmerge Is_Ogee
56.774400,22.000000,2.6,0, 35, 35, , , 0.95, 0, 0,0,,
 9340.61 9378.19 9388.19 9458.19 9468.19 9488.19 9498.19 9538.19 9548.19 9598.19
 9628.19 9668.19 9698.19 9768.20 9848.22 9858.22 9868.23 9918.24 9928.24 9938.24
 9948.29 9967.76 9967.7610031.4110031.4110053.8610079.5110109.7910119.2110149.88
10189.8910249.9010299.9010339.9110377.49
   61.85   61.13   61.02   59.64   59.30   59.04   58.77   58.02   57.91   57.02
   56.40   55.89   55.22   54.10   53.00   52.93   52.69   52.35   52.41   52.27
   52.28   52.15   52.15   51.96   51.96   51.89   51.34   51.06   51.04   51.48
   51.64   51.26   51.22   51.66   52.54
 -938.15 -938.87 -938.98 -940.36 -940.70 -940.96 -941.23 -941.98 -942.09 -942.98
 -943.60 -944.11 -944.78 -945.90 -947.00 -947.07 -947.31 -947.65 -947.59 -947.73
 -947.72 -947.85   49.65   49.46 -948.04 -948.11 -948.66 -948.94 -948.96 -948.52
 -948.36 -948.74 -948.78 -948.34 -947.46
 9340.61 9378.19 9388.19 9458.19 9468.19 9488.19 9498.19 9538.19 9548.19 9598.19
 9628.19 9668.19 9698.19 9768.20 9848.22 9858.22 9868.23 9918.24 9928.24 9938.24
 9948.29 9965.36 9965.3610029.0110029.0110053.8610079.5110109.7910119.2110149.88
10189.8910249.9010299.9010339.9110377.49
   61.85   61.13   61.02   59.64   59.30   59.04   58.77   58.02   57.91   57.02
   56.40   55.89   55.22   54.10   53.00   52.93   52.69   52.35   52.41   52.27
   52.28   52.16   52.16   51.97   51.97   51.89   51.34   51.06   51.04   51.48
   51.64   51.26   51.22   51.66   52.54
 -938.15 -938.87 -938.98 -940.36 -940.70 -940.96 -941.23 -941.98 -942.09 -942.98
 -943.60 -944.11 -944.78 -945.90 -947.00 -947.07 -947.31 -947.65 -947.59 -947.73
 -947.72 -947.84   49.66   49.47 -948.03 -948.11 -948.66 -948.94 -948.96 -948.52
 -948.36 -948.74 -948.78 -948.34 -947.46
Pier Skew, UpSta & Num, DnSta & Num=  ,9999.59, 2 ,9997.18, 2 , 0 , 0 , 0 ,,
    3.00    3.00
 -947.94   52.06
    3.00    3.00
 -947.94   52.06
BR Coef=-1 , 0 , 0 ,, 0 ,,,0.8,0,1,0,
WSPro=,,,, 1 ,,,, 0 ,,,, 0 ,,,,-1 ,-1 ,-1 , 0 , 0 , 0 , 0 , 0
BC Design=,, 0 ,, 0 ,,,,,,

Type RM Length L Ch R = 1 ,4804.895,276.710900,276.710900,276.710900
XS GIS Cut Line= 2
990934.282966703757190.922340155990902.131524444756097.773301706
#Sta/Elev= 30
9262.23864.393699358.20262.324139378.21163.131139418.22860.937629498.26260.11371
9508.26758.815549568.29357.155079638.32356.905959728.36254.612659788.38855.07846
9798.39257.148969868.42253.94873 9908.4453.313979928.44854.60849 9978.4735.67323
9988.47433.144519998.47932.3666910018.49 35.454610028.4940.75442 10038.543.15725
10078.5146.6632110098.52 47.441210108.5346.3109310198.5746.4728910218.5750.31529
10228.5848.71977 10278.647.73164 10288.648.9489910318.62 49.116110355.8652.85137
#Mann= 3 , 0 , 0
9262.238    0.12       09262.238    0.12       010355.86    0.12       0
#XS Ineff= 2 , 0
       09918.014        10074.63       0
Bank Sta=9262.238,10355.86
Exp/Cntr=0.3,0.1

Type RM Length L Ch R = 1 ,4528.184,493.988900,493.988900,493.988900
XS GIS Cut Line= 2
991571.953239113 756767.59501645990912.848671824756060.263285682
#Sta/Elev= 30
9381.68954.73604 9439.9153.249719523.90652.817269549.25851.826569641.25651.77274
9672.27550.660179685.94451.477969740.61849.881379773.27450.518739795.29248.41619
 9808.9648.057849846.61750.740679863.63449.750699890.97151.540179905.29250.47457
9934.62951.071999945.64648.393189959.31439.503199978.63537.787129993.30431.47395
10000.3229.7168910027.6638.9866710037.3139.8307910068.6640.5693610082.3341.76096
10191.6842.6883110246.3541.8355410260.02 42.490510286.6847.1853510348.5151.23054
#Mann= 3 , 0 , 0
9381.689    0.12       09381.689    0.12       010348.51    0.12       0
#XS Ineff= 2 , 0
       0                10134.82       0
Bank Sta=9381.689,10348.51
Exp/Cntr=0.3,0.1

Type RM Length L Ch R = 1 ,4034.195,493.988900,493.988900,493.988900
XS GIS Cut Line= 6
991719.700532389755816.105555871991480.955724874755835.834419109
991395.922904755755874.541578765991219.337769289756004.831165912
991103.414736498756029.147974875990976.321032023756026.921373721
#Sta/Elev= 30
9599.18541.702459633.90541.316859744.06942.28001 9764.2442.722379784.41143.85836
9825.393 43.12949846.18944.106999934.26544.086239950.83131.76392 9959.7528.42934
 9997.8929.0104610040.6428.1729110050.0329.9236510071.0432.2906110107.3834.29743
10126.9136.6470910137.7935.9207810159.3335.5678610169.7333.6304710180.1332.85553
10211.1833.9727910261.7733.8639710301.9334.4576510311.9435.6143910331.9641.13049
10341.9743.1055310351.97 42.723210361.9843.2809610372.0246.7107810400.8347.66675
#Mann= 3 , 0 , 0
9599.185    0.12       09599.185    0.12       010400.83    0.12       0
#XS Ineff= 2 , 0
       09687.452        10321.49       0
Bank Sta=9599.185,10400.83
Exp/Cntr=0.3,0.1

Type RM Length L Ch R = 1 ,3540.206,493.988800,493.988800,493.988800
XS GIS Cut Line= 6
991609.283558865 755635.43756942991411.149615823755634.341313153
991315.998948721755618.586770163991261.424073845  755592.7477102
 991107.65744764755488.554053762990864.001048157755397.391300597
#Sta/Elev= 30
9599.10539.632439613.38839.349199663.38840.117969683.38840.755069693.38840.34123
9773.39842.364099843.624 42.01199863.97636.642889874.20935.91335  9884.636.83356
9895.03336.425989916.62331.369979967.49428.1840210001.0124.52824 10012.424.69807
   1002527.16381 10033.929.56405 10037.630.9075210050.3438.8755710062.7942.81177
10109.78 42.478610132.3442.8052510185.6742.7608510226.57 41.882210241.1442.09304
10251.7841.7338610336.4143.1369310368.1442.4798710378.7242.7740310400.9442.11837
#Mann= 3 , 0 , 0
9599.105    0.12       09599.105    0.12       010400.94    0.12       0
#XS Ineff= 2 , 0
       0                               0
Bank Sta=9599.105,10400.94
Exp/Cntr=0.3,0.1

Type RM Length L Ch R = 1 ,3046.217,493.988900,493.988900,493.988900
XS GIS Cut Line= 6
991725.248286812755106.518873411991583.788952471755099.932939238
991383.293853534755095.732491889991274.626017952 755089.19480155
991078.135193737755087.909242579990924.260702756755075.302238259
#Sta/Elev= 30
9599.01435.03247 9679.3536.664569709.38236.332679779.42438.717949799.42937.63057
9809.43139.151869819.433 38.75219829.43540.173339879.44638.271789899.45139.14498
9919.45538.112629939.45938.296779959.49239.77818 9969.5137.955139979.52731.18092
9989.54526.988469999.56220.69611 10019.623.4340210059.6625.2304610079.6631.28587
10119.6636.8128210139.6638.4820910189.6638.1719510199.6639.3550210239.6638.38738
10299.7539.6501810309.7641.1178310339.8838.4758610390.16 38.477410400.9637.66497
#Mann= 3 , 0 , 0
9599.014    0.12       09599.014    0.12       010400.96    0.12       0
#XS Ineff= 2 , 0
       09685.861                       0
Bank Sta=9599.014,10400.96
Exp/Cntr=0.3,0.1

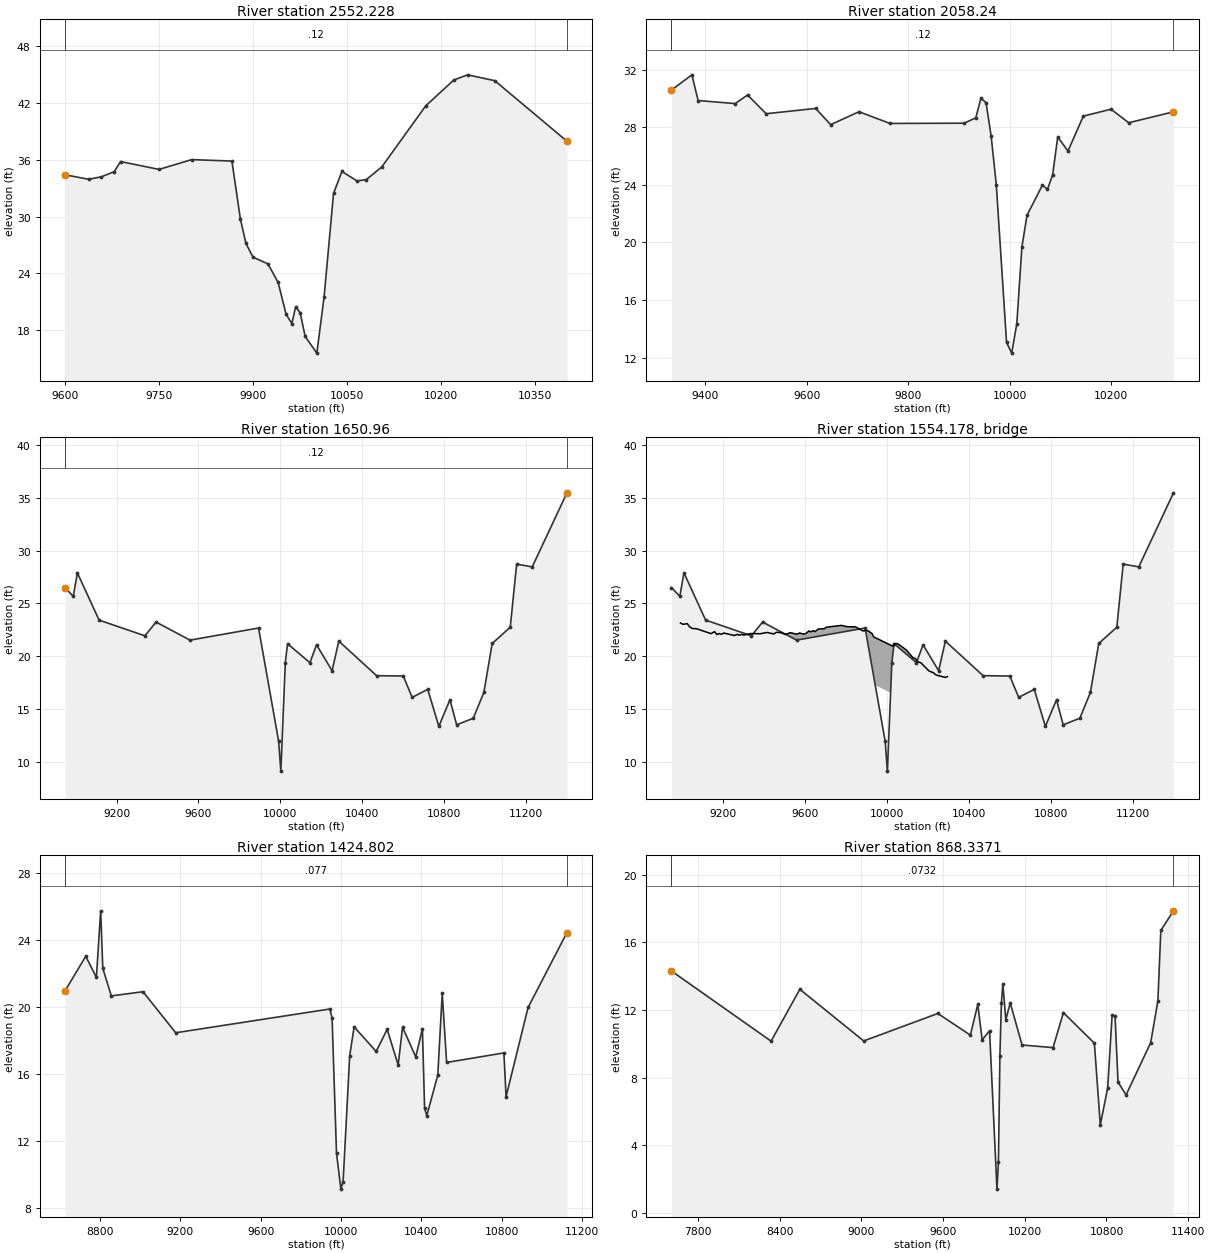
Type RM Length L Ch R = 1 ,2552.228,493.988900,493.988900,493.988900
XS GIS Cut Line= 6
991652.519489362754777.257926363991498.372965717754746.609989921
991389.429185351754708.518827339991331.512991103754673.381949515
 991164.41955588754540.891914821990936.977618813754444.133290444
#Sta/Elev= 30
9599.11634.397379637.22233.924029657.53534.188069677.84834.723359688.01235.78936
9749.52834.964869801.54935.99476 9865.8635.842429879.325 29.76319888.23427.17671
9899.576 25.71879923.43925.009869939.69623.051189952.43719.689239961.62118.72835
9967.638 20.48879974.89819.867899982.83917.3711510001.5115.6106810013.0921.52969
10028.1832.4339510041.5634.7470210065.7533.7495210080.5433.8893510105.4335.24149
10175.4241.6581210220.2244.3809510242.16 44.927410285.7444.3087110400.9437.93449
#Mann= 3 , 0 , 0
9599.116    0.12       09599.116    0.12       010400.94    0.12       0
#XS Ineff= 2 , 0
       0                10245.76       0
Bank Sta=9599.116,10400.94
Exp/Cntr=0.3,0.1

Type RM Length L Ch R = 1 , 2058.24,407.279100,407.279100,407.279100
XS GIS Cut Line= 4
991998.068356663754544.170871153991511.957245529754205.629204497
991273.241967797754175.247260034991138.693356633754253.372260034
#Sta/Elev= 30
9333.796 30.58069374.093 31.6415 9386.2829.855689459.39629.644649483.768 30.2414
9520.327 28.94059617.81629.306869647.30928.180729703.11829.078279764.04928.26506
9910.28228.28214 9933.1928.65658 9943.2730.015799953.35129.703449963.43227.36506
9973.51223.998369993.67413.0631910003.7512.3124210013.8414.3413910023.92 19.6911
   1003421.8871910064.2423.9737710074.3223.69125 10084.424.6903910094.4827.32811
10114.6426.3461310144.8828.7755210199.4729.2532410234.1728.31353 10322.429.07072
#Mann= 3 , 0 , 0
9333.796    0.12       09333.796    0.12       0 10322.4    0.12       0
#XS Ineff= 2 , 0
       0 9846.65        10247.76       0
Bank Sta=9333.796,10322.4
Exp/Cntr=0.3,0.1

Type RM Length L Ch R = 1 , 1650.96,226.158800,226.158800,226.158800
XS GIS Cut Line= 5
992265.370569021754349.724323153992113.432799786754085.058531567
991150.343391448753673.356189087990276.334326535753305.591335788
990128.439362764753286.159938395
#Sta/Elev= 30
8948.08526.50531    898925.670459009.08627.893929114.962 23.42039338.56121.93611
9392.93823.236439558.69821.525189893.20522.672029991.084 11.960510001.969.124815
10023.7119.4020310034.5921.1844810143.8319.3870810175.9721.0828210252.0918.62782
10284.7221.4322310469.1918.1596810599.3818.1277810642.78 16.104710718.7316.86785
10772.9713.3597910827.2215.8874510859.7713.5105110941.0114.1303610992.5816.57118
11033.3521.20743 11121.522.7469811152.6928.7223811228.6428.4579111398.0635.46951
#Mann= 3 , 0 , 0
8948.085    0.12       08948.085    0.12       011398.06    0.12       0
#XS Ineff= 2 , 0
       09839.975        10312.95       0
Bank Sta=8948.085,11398.06
Exp/Cntr=0.3,0.1

Type RM Length L Ch R = 3 ,1554.178,,,
BEGIN DESCRIPTION:
END DESCRIPTION:
Bridge Culvert--1,0,-1,-1, 0
Deck Dist Width WeirC Skew NumUp NumDn MinLoCord MaxHiCord MaxSubmerge Is_Ogee
103.729400,18.700000,2.6,0, 60, 60, , , 0.95, 0, 0,0,,
 8991.90 9005.03 9025.14 9036.28 9050.51 9069.68 9141.48 9158.75 9169.89 9181.02
 9192.16 9203.29 9255.18 9270.10 9277.92 9292.36 9300.66 9336.90 9381.44 9414.84
 9448.24 9459.85 9482.59 9503.92 9528.07 9559.59 9573.56 9592.99 9604.12 9619.04
 9626.39 9641.78 9648.66 9664.52 9693.20 9704.33 9778.22 9804.54 9846.45 9882.48
 9904.75 9927.02 9934.52 9943.57 9943.5710016.7310016.7310027.5610038.3610051.12
10094.0310127.4410138.5710149.7010164.8210205.3810227.6410238.7810283.3210294.76
   23.15   23.02   23.09   22.79   22.62   22.61   22.14   22.33   22.05   22.15
   22.07   22.20   21.96   22.08   21.99   22.07   22.00   22.15   22.13   22.25
   22.11   22.27   22.23   22.06   22.23   22.09   22.20   22.10   22.15   22.40
   22.31   22.42   22.33   22.58   22.60   22.75   22.92   22.80   22.78   22.40
   22.44   22.15   21.84   21.75   21.75   21.06   21.06   20.95   21.19   21.20
   20.60   19.84   19.79   19.48   19.39   18.60   18.43   18.23   18.00   18.07
 -976.85 -976.98 -976.91 -977.21 -977.38 -977.39 -977.86 -977.67 -977.95 -977.85
 -977.93 -977.80 -978.04 -977.92 -978.01 -977.93 -978.00 -977.85 -977.87 -977.75
 -977.89 -977.73 -977.77 -977.94 -977.77 -977.91 -977.80 -977.90 -977.85 -977.60
 -977.69 -977.58 -977.67 -977.42 -977.40 -977.25 -977.08 -977.20 -977.22 -977.60
 -977.56 -977.85 -978.16 -978.25   17.25   16.56 -978.94 -979.05 -978.81 -978.80
 -979.40 -980.16 -980.21 -980.52 -980.61 -981.40 -981.57 -981.77 -982.00 -981.93
 8991.90 9005.03 9025.14 9036.28 9050.51 9069.68 9141.48 9158.75 9169.89 9181.02
 9192.16 9203.29 9255.18 9270.10 9277.92 9292.36 9300.66 9336.90 9381.44 9414.84
 9448.24 9459.85 9482.59 9503.92 9528.07 9559.59 9573.56 9592.99 9604.12 9619.04
 9626.39 9641.78 9648.66 9664.52 9693.20 9704.33 9778.22 9804.54 9846.45 9882.48
 9904.75 9927.02 9934.52 9958.01 9958.0110027.5610031.1710031.1710038.3610051.12
10094.0310127.4410138.5710149.7010164.8210205.3810227.6410238.7810283.3210294.76
   23.15   23.02   23.09   22.79   22.62   22.61   22.14   22.33   22.05   22.15
   22.07   22.20   21.96   22.08   21.99   22.07   22.00   22.15   22.13   22.25
   22.11   22.27   22.23   22.06   22.23   22.09   22.20   22.10   22.15   22.40
   22.31   22.42   22.33   22.58   22.60   22.75   22.92   22.80   22.78   22.40
   22.44   22.15   21.84   21.61   21.61   20.95   21.04   21.04   21.19   21.20
   20.60   19.84   19.79   19.48   19.39   18.60   18.43   18.23   18.00   18.07
 -976.85 -976.98 -976.91 -977.21 -977.38 -977.39 -977.86 -977.67 -977.95 -977.85
 -977.93 -977.80 -978.04 -977.92 -978.01 -977.93 -978.00 -977.85 -977.87 -977.75
 -977.89 -977.73 -977.77 -977.94 -977.77 -977.91 -977.80 -977.90 -977.85 -977.60
 -977.69 -977.58 -977.67 -977.42 -977.40 -977.25 -977.08 -977.20 -977.22 -977.60
 -977.56 -977.85 -978.16 -978.39   17.11   16.45   16.54 -978.96 -978.81 -978.80
 -979.40 -980.16 -980.21 -980.52 -980.61 -981.40 -981.57 -981.77 -982.00 -981.93
BR Coef=-1 , 0 , 0 ,, 0 ,,,0.8,0,1,0,
WSPro=,,,, 1 ,,,, 0 ,,,, 0 ,,,,-1 ,-1 ,-1 , 0 , 0 , 0 , 0 , 0
BC Design=,, 0 ,, 0 ,,,,,,

Type RM Length L Ch R = 1 ,1424.802,556.464500,556.464500,556.464500
XS GIS Cut Line= 5
992559.443670779754322.767622158992472.158306867754079.375741839
992336.438235283753957.626854137990597.564174652753172.405416116
990447.018556356753148.925824255
#Sta/Elev= 30
8624.46320.956448728.32723.043758781.44521.782398802.692 25.76448813.31622.32042
 8855.8120.672569013.55520.921799176.65918.465819944.72119.889239955.69319.33191
9977.63811.261219999.5829.10614510010.559.56222710043.4717.1025810065.4218.81802
10175.1417.34865   1023018.6687610284.8616.5395510306.8118.7955310372.6417.02106
10405.5618.7048510416.5313.95392 10427.513.5014410482.3615.9450610504.3120.82524
10526.2516.6893210811.5317.25829 10822.514.6443810932.2319.9828911125.6724.46376
#Mann= 3 , 0 , 0
8624.463   0.077       08624.463   0.077       011125.67   0.077       0
#XS Ineff= 2 , 0
       09873.815        10422.08       0
Bank Sta=8624.463,11125.67
Exp/Cntr=0.3,0.1

Type RM Length L Ch R = 1 ,868.3371,580.674000,580.674000,580.674000
XS GIS Cut Line= 4
 993235.04752332754479.066704482992657.790578902753537.226426691
991707.269745559753129.240315571990279.318356663752530.281982258
#Sta/Elev= 30
7604.47914.310818336.43510.157388547.554 13.22689016.88610.169199560.99811.79543
9800.20810.511589854.42812.326849886.96110.232889941.18110.778019995.4011.396587
10006.252.97976910017.099.29633310027.93 12.399910038.7813.5376210060.4711.43625
   1009312.4212610179.759.92828210407.489.77537910483.3811.8449510711.1110.03581
10754.495.20366710808.717.38758910841.2411.6884410862.9311.6464710884.62 7.73758
10943.72 6.9721111124.6910.0699411177.4112.5468511199.0916.7109511292.0117.87203
#Mann= 3 , 0 , 0
7604.479  0.0732       07604.479  0.0732       011292.01  0.0732       0
#XS Ineff= 2 , 0
       09696.927        10462.96       0
Bank Sta=7604.479,11292.01
Exp/Cntr=0.3,0.1

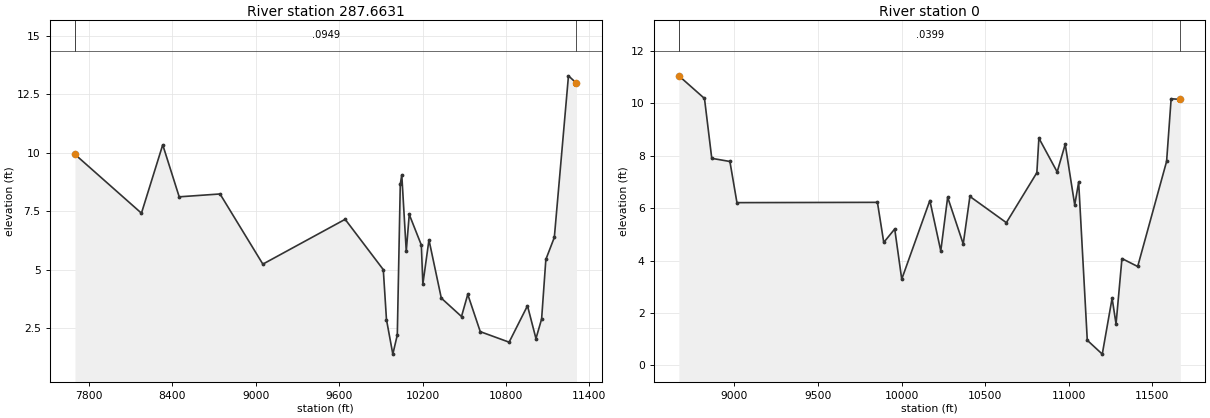
Type RM Length L Ch R = 1 ,287.6631,287.663100,287.663100,287.663100
XS GIS Cut Line= 6
993321.853078902754170.906982243992653.450301111753098.858371153
992380.012801081752890.525037795991784.977659017752559.981010452
991082.427449346752225.798168346990548.415578872752126.636148915
#Sta/Elev= 30
7698.2989.9352648176.6367.4240548329.83410.34512 8448.39 8.122838742.2898.245075
9050.5155.2470959642.8817.1623719917.4255.0119849940.3042.8777359986.0611.402474
10018.242.22199910039.748.66097110050.499.05933210082.745.79748510104.257.369566
10191.276.06270610202.244.39522510246.126.28503910334.943.79544110480.383.009469
10525.413.95472510615.452.36259510823.071.913046 10955.33.46890611016.32  2.0663
11057.012.90458211087.525.44765711148.546.38965711250.2513.2923911307.8112.97872
#Mann= 3 , 0 , 0
7698.298  0.0949       07698.298  0.0949       011307.81  0.0949       0
#XS Ineff= 2 , 0
       09889.681        10449.63       0
Bank Sta=7698.298,11307.81
Exp/Cntr=0.3,0.1

Type RM Length L Ch R = 1 ,       0,0.000000,0.000000,0.000000
XS GIS Cut Line= 6
993065.776689976752886.184760034992323.589190036 752595.38614893
991980.707245529 752400.07364893991498.936412215751992.087537795
991208.137801111751571.080593348990648.241967767751918.302815586
#Sta/Elev= 30
8668.24711.043458821.40810.179738864.9267.897764 8973.467.7770739015.5436.208188
9855.6286.2193469893.5014.692006 9959.045.203238   100013.28977810169.156.289237
10234.47 4.36641 10275.66.41385210368.754.63174410408.676.44458110626.675.444959
10809.037.34925310821.188.66753510930.567.37916110978.588.43430711035.476.119612
11059.01 6.9903211110.550.96028711200.210.43203211259.042.56393211282.581.581005
11317.884.07644111412.013.77358911584.917.78141611612.0510.1691411667.0710.14461
#Mann= 3 , 0 , 0
8668.247  0.0399       08668.247  0.0399       011667.07  0.0399       0
#XS Ineff= 2 , 0
       09911.465        10209.59       0
Bank Sta=8668.247,11667.07
Exp/Cntr=0.3,0.1